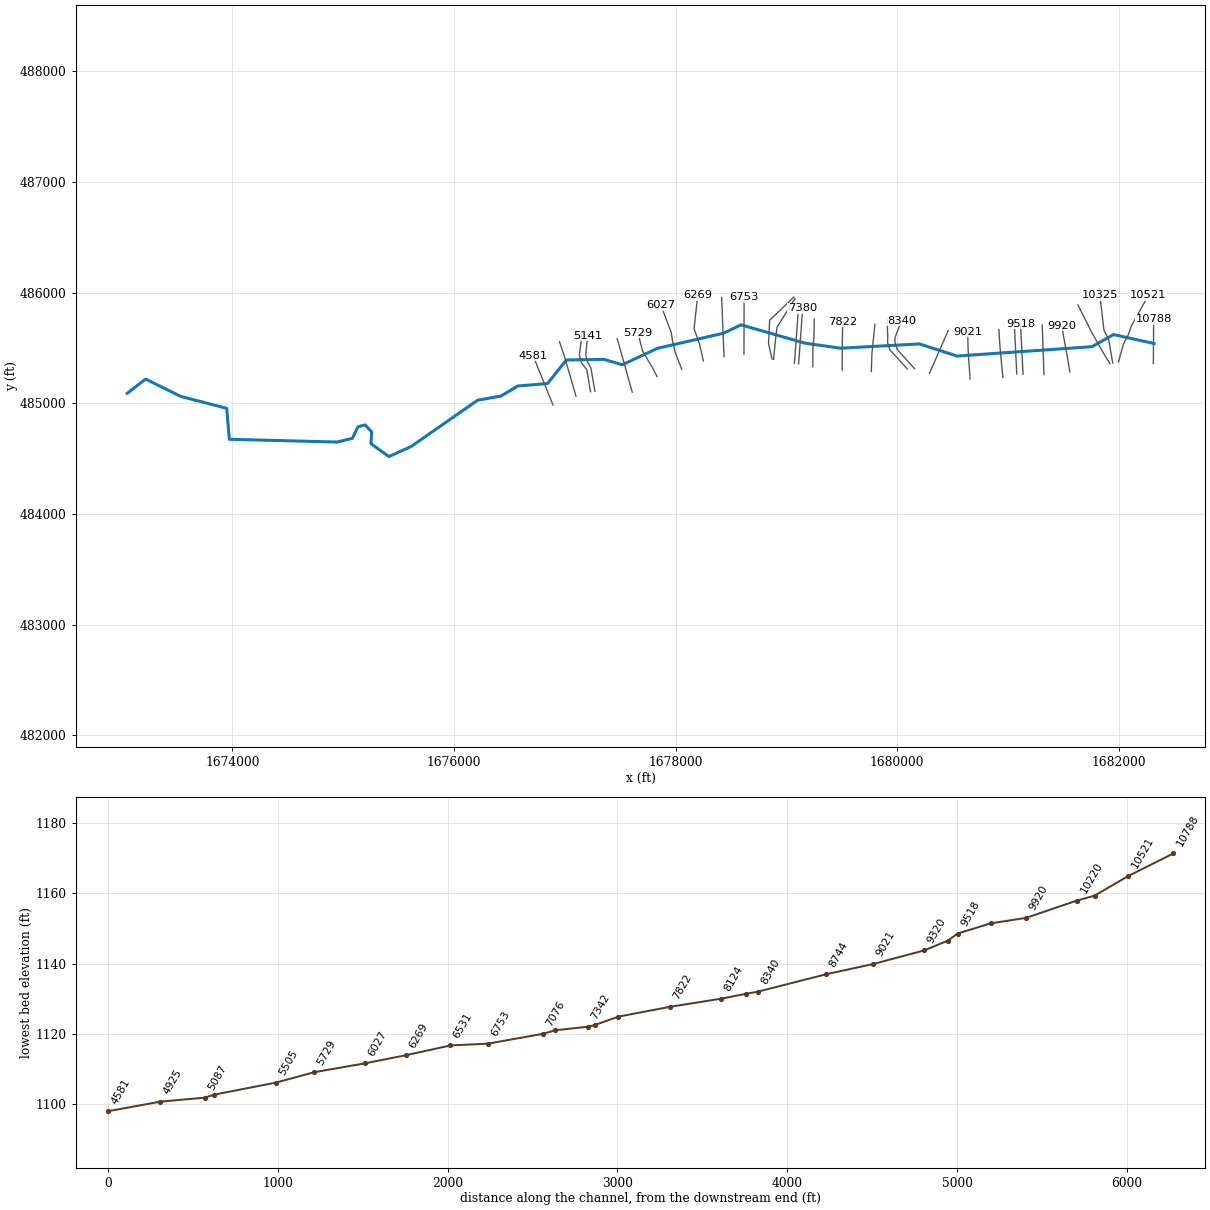
--- GraveCk2.prj (project) ---

Proj Title=GraveCk2
Current Plan=p01
Default Exp/Contr=0,0
English Units
Geom File=g01
Flow File=f01
Plan File=p01
BEGIN DESCRIPTION:
---------- MODELED AS PART OF WVEM CTP PROGRAM, 2025----------
Stream Name: Grave Creek
Flood Zone: AFH
Marshall County, WV
HEC-RAS Version: RAS 6.6
Vertical Datum: NAVD88
Projection: NAD 1983 StatePlane West Virginia N FIPS 4701 (US Feet)
Terrain: 1-meter West Virginia FEMA R3 South Central (collected 2018-2019)
Land Use: 2024 NLCD
Hydrologic Method:
Duda et al., "Estimation of magnitude and frequency of floods for rural, unregulated streams in and near Virginia and West Virginia." September 8, 2025.
Additional Model Notes:
KWSEL AE
END DESCRIPTION:
DSS Export Rating Curves= 0
DSS Export Rating Curve Sorted= 0
DSS Export Volume Flow Curves= 0
DXF OffsetX= 0
DXF OffsetY= 0
DXF ScaleX= 0
DXF ScaleY= 0

--- GraveCk2.p01 (plan) ---

Plan Title=Floodplain
Program Version=6.60
Short Identifier=Floodplain
Geom File=g01
Flow File=f01
Subcritical Flow
K Sum by GR= 0
Std Step Tol= 0.01
Critical Tol= 0.01
Num of Std Step Trials= 20
Max Error Tol= 0.3
Flow Tol Ratio= 0.001
Split Flow NTrial= 30
Split Flow Tol= 0.02
Split Flow Ratio= 0.02
Log Output Level= 0
Friction Slope Method= 1
Unsteady Friction Slope Method= 2
Unsteady Bridges Friction Slope Method= 1
Parabolic Critical Depth
Global Vel Dist= 0 , 0 , 0
Global Log Level= 0
CheckData=False
Encroach Param=-1 ,0,0, 0
Flow Ratio Tolerance=0.1
Flow Ratio Min Ratio=0.5
Flow Ratio Max Ratio=4
Flow Ratio Max Iterations= 10
Mapping Interval=1HOUR
Computation Time Step Use Courant=        0
Computation Time Step Use Time Series=    0
Computation Time Step Count To Double=0
Computation Time Step Max Doubling=0
Computation Time Step Max Halving=0
Computation Time Step Residence Courant=0
Run HTab= 0
Run UNet= 0
Run Sediment= 0
Run PostProcess= 0
Run WQNet= 0
Run RASMapper=-1
UNET Theta= 0
UNET Theta Warmup= 0
UNET ZTol= 0
UNET ZSATol= 0
UNET MxIter= 0
UNET Max Iter WO Improvement= 0
UNET MaxInSteps= 0
UNET DtIC= 0
UNET DtMin= 0
UNET MaxCRTS= 0
UNET WFStab= 0
UNET SFStab= 0
UNET WFX= 1
UNET SFX= 1
UNET Gravity=32.17405
UNET 1D Methodology=Finite Difference
UNET DSS MLevel= 1
UNET Pardiso=0
UNET DZMax Abort= 0
UNET Use Existing IB Tables= 0
UNET Froude Reduction=False
UNET Froude Limit= 0
UNET Froude Power= 0
UNET D1 Cores= 0
UNET WindReference=Eulerian
UNET WindDragFormulation=Hsu (1988)
UNET D2 Coriolis=0
UNET D2 Cores= 0
UNET D2 Theta= 1
UNET D2 Theta Warmup= 1
UNET D2 Z Tol= 0.01
UNET D2 Volume Tol= 0.01
UNET D2 Max Iterations= 20
UNET D2 Advanced Convergence=0
UNET D2 WS Max Tol=0.15
UNET D2 WS RMS Tol=0.002
UNET D2 WS Stall Tol=1
UNET D2 Equation= 0
UNET D2 RampUpFraction=0.1
UNET D2 TimeSlices= 1
UNET D2 Turbulence Formulation=Non-Conservative (original)
UNET D2 Eddy Viscosity=0.3
UNET D2 Transverse Eddy Viscosity=0.1
UNET D2 Smagorinsky Mixing=0
UNET D2 BCVolumeCheck=0
UNET D2 Cores=0
UNET D2 SolverType=PARDISO (Direct)
UNET D2 Minimum Iterations= 3
UNET D2 Maximum Iterations= 30
UNET D2 Restart Number= 10
UNET D2 Relaxation Coeff=1.3
UNET D2 SOR Precondition Iterations= 10
UNET D2 ILUT Maximum Fill= 8
UNET D2 ILUT Tolerance=1E-08
UNET D2 Convergence Tolerance=0.00001
PS Theta= 1
PS WS Tol= 0.01
PS Volume Tol= 0.01
PS Max Iterations= 20
PS Equation= 0
PS Advance Time Step=-1
PS Target Courant=0.9
PS Time Slices= 1
PS Iterate With 2D=0
PS Project Initial WSE from DS=-1
PS Ramp Up Initial WSE from US=-1
PS Cores=0
UNET D1D2 MaxIter= 0
UNET D1D2 ZTol=0.01
UNET D1D2 QTol=0.1
UNET D1D2 MinQTol=1
Write IC File= 0
Write IC File at Fixed DateTime=0
Write IC File at Sim End=0
Echo Input=False
Echo Parameters=False
Echo Output=False
Write Detailed= 0
HDF Write Warmup=0
HDF Write Time Slices=0
HDF Flush=0
HDF Compression= 1
HDF Chunk Size= 1
HDF Spatial Parts= 1
HDF Use Max Rows=0
HDF Fixed Rows= 1
Calibration Method= 0
Calibration Iterations= 20
Calibration Max Change=0.05
Calibration Tolerance=0.2
Calibration Maximum=1.5
Calibration Minimum=0.5
Calibration Optimization Method= 1
WQ AD Non Conservative
WQ ULTIMATE=-1
WQ Max Comp Step=1HOUR
WQ Output Interval=15MIN
WQ Output Selected Increments= 0
WQ Create Restart=0
WQ Fixed Restart=0
WQ System Summary=0
WQ Write To DSS=0
Sorting and Armoring Iterations= 10
XS Update Threshold= 0.02
Bed Roughness Predictor= 0
Processes Affected by Predictor=Sediment Only
Hydraulics Update Threshold= 0.02
Energy Slope Method= 1
Volume Change Method= 1
Sediment Retention Method= 0
Sediment TS Multiplier= 1
Warm Up Method= 0
XS Weighting Method= 0
Number of US Weighted Cross Sections= 1
Number of DS Weighted Cross Sections= 1
Upstream XS Weight=0
Main XS Weight=1
Downstream XS Weight=0
Number of DS XS's Weighted with US Boundary= 1
Upstream Boundary Weight= 1
Weight of XSs Associated with US Boundary= 0
Number of US XS's Weighted with DS Boundary= 1
Downstream Boundary Weight= 0.5
Weight of XSs Associated with DS Boundary= 0.5
Percentile Method= 0
Sediment Output Level= 3
Mass or Volume Output= 0
Output Increment Type= 1
Profile and TS Output Increment= 1
Transport Output Increment 1
XS Output Flag= 0
XS Output Increment= 10
Read HDF5 Sediment Hotstart= 0
Sediment Hotstart Type= 0
Write Gradation File= 0
Read Gradation Hotstart= 0
Write HDF5 File= 1
Write Binary Output= 1
Write DSS Sediment File= 0
DSS Sediment Output Type= 1
SV Curve= 0
Specific Gage Flag= 0
Subcell Erosion Methods= 0
Subcell Deposition Methods= 0
Advection Scheme= 1
Matrix Solver= 0
Implicit Weighting Factor= 1
Maximum Outer Loop Convergence Iterations= 5
Convergence Maximum Absolute= 0.001
Convergence RMSE= 0.0001
Grain Fractions Max Abs Error= 0.001
Max Subgrid Regions= 1
Max Subgrid Length Scale= 3.402823E+38
Initial Layer Thickness= 3
Min Layer Thickness= 0.1
Max Layer Thickness= 6
Number of Layers= 5

--- GraveCk2.f01 (steady flow) ---

Flow Title=Flow
Program Version=6.60
Number of Profiles= 1
Profile Names=P100yr
River Rch & RM=GraveCk2,Main            ,10788
     776
River Rch & RM=GraveCk2,Main            ,6753
     781
River Rch & RM=GraveCk2,Main            ,6269
     938
River Rch & RM=GraveCk2,Main            ,3734
    1050
River Rch & RM=GraveCk2,Main            ,3437
    1290
Boundary for River Rch & Prof#=GraveCk2,Main            , 1
Up Type= 0
Dn Type= 1
Dn Known WS=1074.4
DSS Import GetInterval= 0
DSS Import GetPeak= 0
DSS Import FillOption= 0

--- GraveCk2.g01 (geometry) ---

Geom Title=Geometry
Program Version=6.60

River Reach=GraveCk2        ,Main
Reach XY= 30
1682318.23360283485539.931636812      1681952.92      485621.001
     1681757.677       485511.32     1680540.053      485426.589
     1680201.069       485536.19        1679488.        485497.6
     1679166.104      485543.348     1678591.347      485708.714
     1678431.988       485632.61     1677835.968      485496.192
     1677519.312      485348.038     1677352.195      485396.971
     1677013.811      485390.855     1676844.959      485178.445
     1676575.639      485156.165     1676423.247      485064.857
     1676214.797      485028.514       1675614.4      484610.288
      1675413.39       484518.94     1675250.816      484635.392
     1675257.685       484742.03     1675197.824      484804.835
      1675133.71      484787.826     1675083.662      484683.477
     1674945.621      484650.112      1673972.91      484675.053
     1673949.313       484954.69     1673534.415      485062.245
     1673217.502      485219.011  1673051.846485485090.494510165

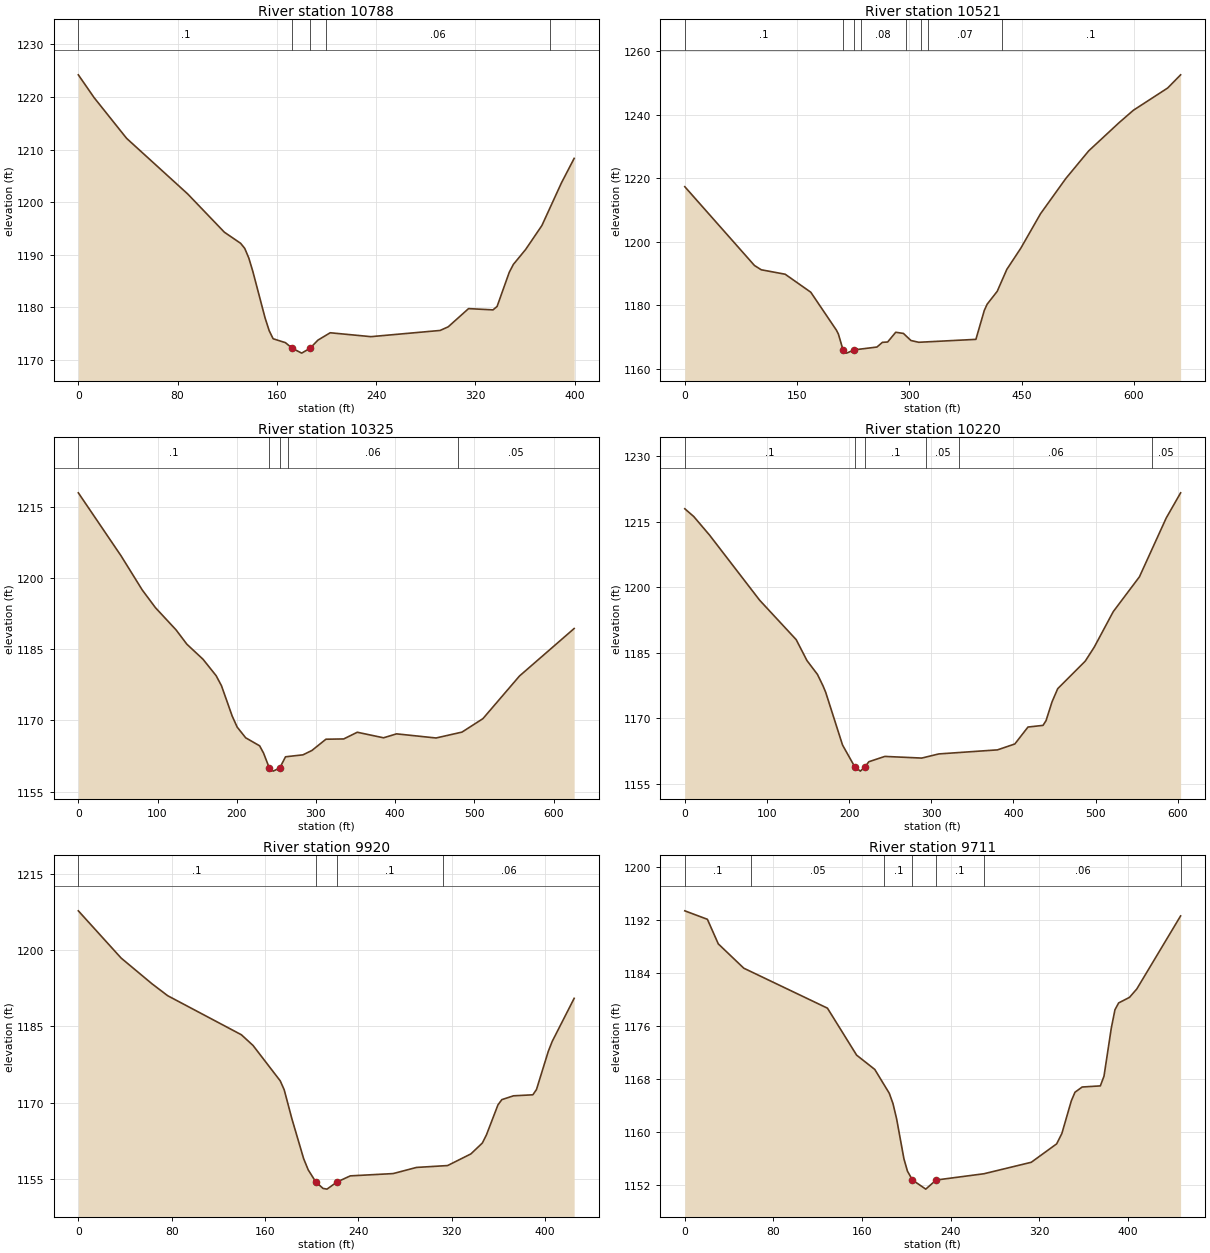
Type RM Length L Ch R = 1 ,10788   ,266.3,266.9,259.2
XS GIS Cut Line= 2
1682311.56878483485358.5600094341682314.62341305485758.101455407
#Sta/Elev= 30
       0  1224.2    12.7 1219.87    38.9 1212.13    88.1 1201.57   117.7 1194.29
   130.8 1192.18   134.1 1191.22   137.4 1189.38   140.6 1186.87   150.5 1178.01
   153.8 1175.58     157 1174.04   166.9  1173.3  172.36 1172.24     180 1171.31
  186.771172.239   193.1 1173.78     203 1175.18   235.8 1174.44   291.6 1175.62
   298.1 1176.31   314.5 1179.77   334.2 1179.53   337.5 1180.19   347.3 1186.67
   350.6 1188.17   360.5 1191.01   373.6 1195.56   389.4 1203.69   399.6 1208.32
#Mann= 5 ,-1,0
       0      .1       0  172.36    .045       0  186.77      .1       0
     200     .06       0     380      .1       0
Bank Sta=172.36,186.77
XS Rating Curve= 0 ,0
Exp/Cntr=0.3,0.1

Type RM Length L Ch R = 1 ,10521   ,196.6,196.6,196.6
XS GIS Cut Line= 6
1681996.76842017485373.4127530011682020.53576109485459.095980585
1682041.37266168485532.1348765051682086.66226926 485621.54775542
1682111.68420084485695.5518725071682267.09363241485974.327133874
#Sta/Elev= 30
       0 1217.34    93.1 1192.49   102.2 1191.14   134.1 1189.74   168.3 1184.07
   202.5 1172.12   205.2 1170.88  211.441165.858   216.2 1164.86   226.1 1165.88
   256.7 1166.78     264 1168.26     271 1168.37   281.8 1171.44   292.1 1171.07
   302.1 1168.84   312.6 1168.28   388.9  1169.2   400.1 1178.31   403.9 1180.28
   417.4 1184.36   430.2 1191.26     449 1197.99   475.2  1208.8     509 1219.92
   539.6 1228.64   579.9 1237.47   599.2 1241.43   645.1 1248.46   662.4 1252.62
#Mann= 8 ,-1,0
       0      .1       0  211.44    .045       0   226.1     .07       0
  234.87     .08       0   295.1     .07       0   315.1     .08       0
   325.1     .07       0  423.22      .1       0
Bank Sta=211.44,226.1
XS Rating Curve= 0 ,0
Exp/Cntr(USF)=0,0
Exp/Cntr=0.3,0.1

Type RM Length L Ch R = 1 ,10325   ,104.7,104.7,104.7
XS GIS Cut Line= 4
1681945.33697887485363.8751769511681908.50186154485574.968733972
1681865.99980308485659.9728508931681829.16468575  485974.4880835
#Sta/Elev= 30
       0 1217.93    54.1 1204.62    80.7 1197.47    97.4 1193.73   123.4 1189.06
     137 1186.05   157.5 1182.86     174 1179.41   180.7 1177.31   194.3 1170.89
   200.6 1168.57   211.3 1166.33   228.9 1164.64   233.8 1163.13   241.1 1159.99
     246 1159.31   254.3 1159.98   261.6 1162.33   283.6 1162.74   294.9 1163.66
   312.6 1166.03   335.1 1166.09   352.2  1167.5   385.3 1166.33   401.8 1167.16
   451.6 1166.29   484.4 1167.53   510.8 1170.36     557 1179.35     626 1189.35
#Mann= 5 ,-1,0
       0      .1       0   241.1    .045       0   254.3      .1       0
  264.28     .06       0  479.32     .05       0
Bank Sta=241.1,254.3
XS Rating Curve= 0 ,0
Exp/Cntr(USF)=0,0
Exp/Cntr=0.3,0.1

Type RM Length L Ch R = 1 ,10220   ,301.3,299.7,297.6
XS GIS Cut Line= 6
1681919.39882426 485358.706417591681873.44123901485433.558630094
1681835.22281151485498.6004947571681786.35611135485586.283062175
1681749.45231375485651.5752544251681631.13507059485888.515938428
#Sta/Elev= 30
       0 1218.01    10.9 1216.23    30.1 1211.98    91.1 1197.06   135.6 1188.02
   148.7 1183.23   161.5 1180.05   168.2 1177.45   171.5 1175.96     192 1163.88
  206.861158.892   213.7  1157.9  219.431158.894     224 1160.05   243.5 1161.27
   288.4 1160.89   309.2 1161.84   380.6 1162.77   401.7 1164.12   417.7    1168
     436 1168.38   439.7 1169.47     447 1173.78   453.9 1176.79   487.4  1183.1
   498.4 1186.32   521.5 1194.44   553.4 1202.43     586  1215.9   603.5 1221.66
#Mann= 6 ,-1,0
       0      .1       0  206.86    .045       0  219.43      .1       0
  293.65     .05       0  333.65     .06       0  568.65     .05       0
Bank Sta=206.86,219.43
XS Rating Curve= 0 ,0
Exp/Cntr(USF)=0,0
Exp/Cntr=0.3,0.1

Type RM Length L Ch R = 1 ,9920    ,210,208.9,207.1
XS GIS Cut Line= 6
1681557.87362868485282.4841290861681543.87824984485368.877985179
  1681531.331687485442.8286246661681513.21951851485541.174884677
1681499.69428308485614.9450783431681486.67692067485701.495102093
#Sta/Elev= 30
       0 1207.77    36.7 1198.47    63.3 1193.38    76.6 1191.06   139.8 1183.37
   149.8 1181.26   173.1  1174.3   176.5 1172.54   183.1 1166.83   193.2 1158.96
   197.1 1156.77  203.611154.391   209.8 1153.12   213.2 1152.98  221.831154.392
   233.2 1155.59   269.9 1156.04   289.9 1157.25   316.6 1157.62   336.6 1159.92
   346.4 1162.06   349.9 1163.66   359.8 1169.58   363.1  1170.6   373.1 1171.35
   389.7 1171.55   392.8 1172.59   402.9 1180.09   406.3 1182.07   425.1 1190.54
#Mann= 4 ,-1,0
       0      .1       0  203.61    .045       0  221.83      .1       0
  312.53     .06       0
Bank Sta=203.61,221.83
XS Rating Curve= 0 ,0
Exp/Cntr(USF)=0,0
Exp/Cntr=0.3,0.1

Type RM Length L Ch R = 1 ,9711    ,193.3,193.8,193.7
XS GIS Cut Line= 2
1681324.60656428485259.0035763351681308.73953298485706.039936438
#Sta/Elev= 30
       0 1193.37    20.4 1192.09    30.2 1188.39    53.2 1184.72   128.7 1178.69
     155 1171.61   171.4 1169.45   184.5 1165.85   187.8 1164.31   191.1    1162
   197.7 1155.97   200.9  1154.1  205.421152.768   217.4  1151.4  226.691152.769
   269.9 1153.72   312.6 1155.45   335.5 1158.23   340.2  1159.8   348.7 1164.71
     352 1166.01   358.5  1166.8   374.9 1166.97   378.2 1168.44   384.8 1175.71
   388.1 1178.46   391.4 1179.48   401.2 1180.32   407.8 1181.59   447.3  1192.6
#Mann= 7 ,-1,0
       0      .1       0      60     .05       0     180      .1       0
  205.42    .045       0  226.69      .1       0     270     .06       0
  447.32     .05       0
Bank Sta=205.42,226.69
XS Rating Curve= 0 ,0
Exp/Cntr(USF)=0,0
Exp/Cntr=0.3,0.1

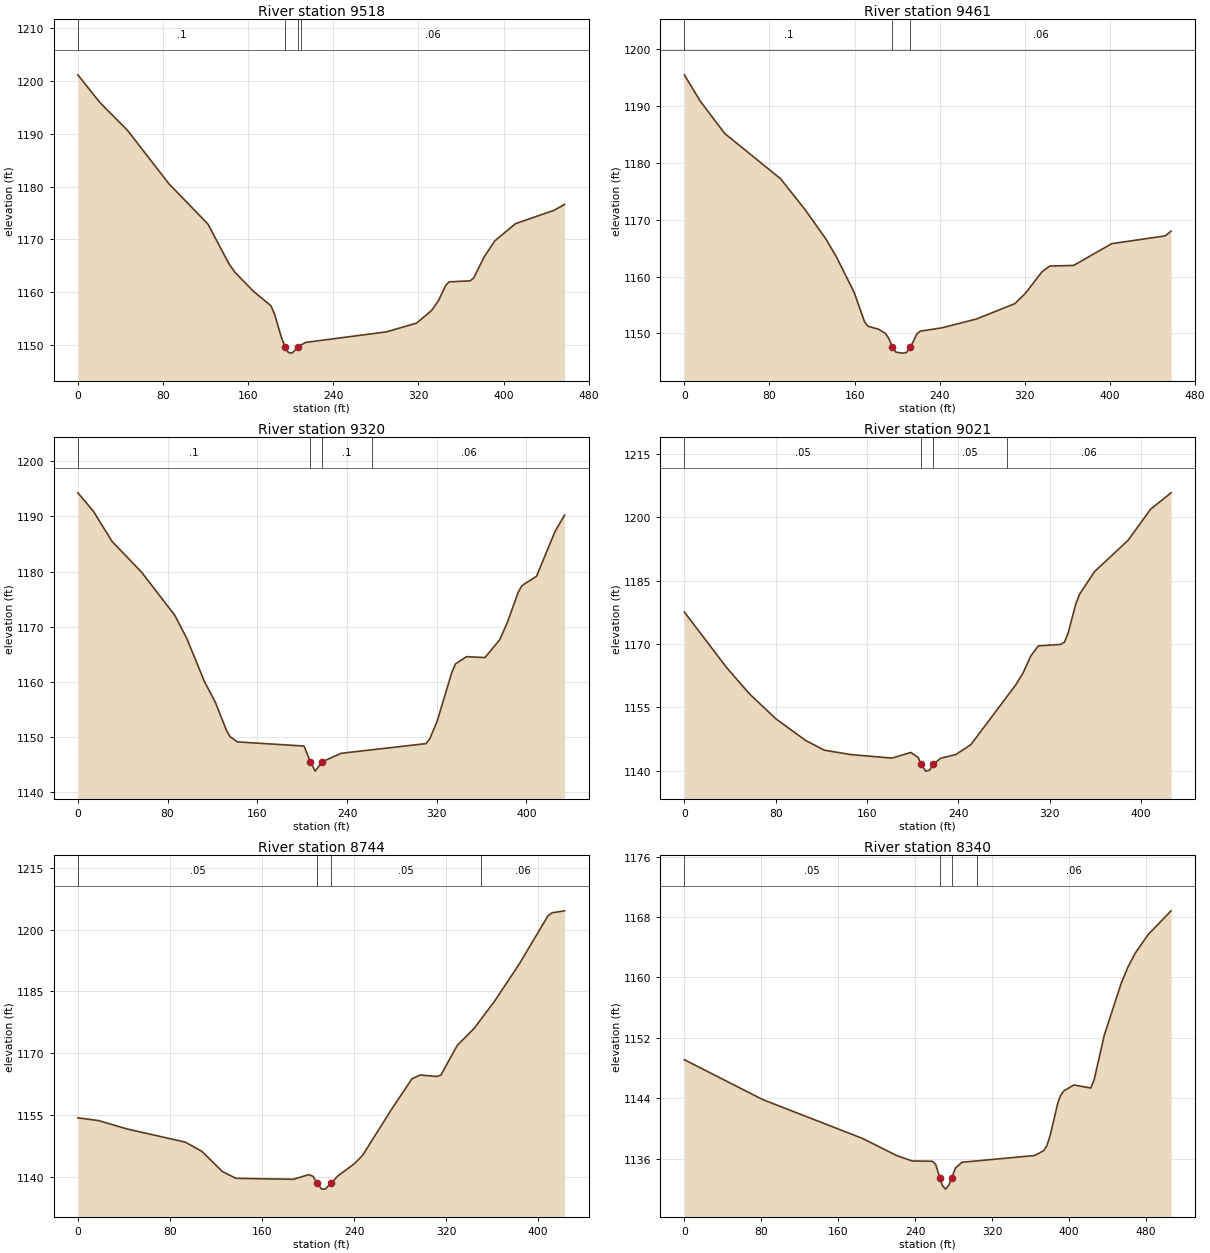
Type RM Length L Ch R = 1 ,9518    ,56.5,56.7,57.2
XS GIS Cut Line= 2
 1681135.5951721485262.2485044081681112.92532004485719.080470095
#Sta/Elev= 30
       0 1201.11    20.4 1195.94    46.7 1190.61    85.5 1180.54   122.3 1172.89
     142  1165.4   147.7 1163.77   164.9 1160.22   181.4 1157.48   184.7 1155.98
   191.2 1151.54  194.871149.617   197.8 1148.64   201.1 1148.52  207.071149.616
     210  1150.1   214.2 1150.55   289.8 1152.53   318.3 1154.19   332.5 1156.59
   339.1 1158.53   345.6  1161.3   348.9 1161.99   368.6 1162.18   371.9 1162.71
   381.8 1166.69   391.6 1169.69   411.3 1172.99   447.5 1175.51   457.4 1176.62
#Mann= 4 ,-1,0
       0      .1       0  194.87    .045       0  207.07      .1       0
     210     .06       0
Bank Sta=194.87,207.07
XS Rating Curve= 0 ,0
Exp/Cntr(USF)=0,0
Exp/Cntr=0.3,0.1

Type RM Length L Ch R = 1 ,9461    ,139.7,140.5,140.6
XS GIS Cut Line= 2
 1681079.3095058485264.4538374341681056.63965375485721.285803122
#Sta/Elev= 30
       0 1195.46    14.9 1190.85    37.9 1185.16    90.5 1177.18   113.5 1171.75
   133.2 1166.56   143.1 1163.39   159.5 1157.25   169.3 1152.07   172.6 1151.26
   182.5 1150.73     189 1150.01   192.3 1149.06  195.591147.525   198.9  1146.7
   204.7 1146.53   208.7 1146.64  212.421147.526   218.6 1149.94   221.9  1150.4
   241.6 1150.96   274.4 1152.52   310.6 1155.23   320.4 1157.02   336.1 1160.83
   343.4 1161.84   365.8 1161.95   401.7 1165.78   451.8 1167.14   457.4 1167.97
#Mann= 3 ,-1,0
       0      .1       0  195.59    .045       0  212.42     .06       0
Bank Sta=195.59,212.42
XS Rating Curve= 0 ,0
Exp/Cntr(USF)=0,0
Exp/Cntr=0.3,0.1

Type RM Length L Ch R = 1 ,9320    ,298.7,299.1,298.3
XS GIS Cut Line= 6
1680953.59366925485232.7158559261680945.42439425485319.833463833
1680938.42211168485394.5062147531680928.85815443485497.091311425
1680923.20823134485575.3605118391680917.79912142485665.149046168
#Sta/Elev= 30
       0  1194.3    13.9 1190.94    30.4 1185.49    56.8 1179.88    86.4 1172.05
    97.1 1167.85   112.8 1160.03   122.7 1156.19   132.5 1151.12   135.8 1149.96
   142.4 1149.03   201.7 1148.28  207.291145.415   211.6 1143.72  217.861145.417
   234.7 1146.96   310.4 1148.72   313.7 1149.57   320.3 1152.76   333.3 1161.56
   336.7 1163.21   346.6 1164.52     363 1164.36   376.2 1167.61   382.7 1170.61
   392.6  1176.2   395.9 1177.42     409 1179.15   425.5 1187.28     434 1190.26
#Mann= 4 ,-1,0
       0      .1       0  207.29    .045       0  217.86      .1       0
   262.5     .06       0
Bank Sta=207.29,217.86
XS Rating Curve= 0 ,0
Exp/Cntr(USF)=0,0
Exp/Cntr=0.3,0.1

Type RM Length L Ch R = 1 ,9021    ,279.5,277.3,273.8
XS GIS Cut Line= 6
1680657.39806743485219.2509878431680652.22780217485306.615314424
1680646.32558301485381.3825533391680640.31772101485481.219295919
1680638.16615051485556.8772810851680635.52278309485645.019165173
#Sta/Elev= 30
       0 1177.57    37.2 1164.35    56.9 1158.22      80  1152.3   106.3 1147.12
   122.7 1144.82   145.8 1143.79   181.9 1142.94   198.4 1144.29   204.9  1143.1
  207.331141.476   211.5 1139.86   214.8 1140.09  218.041141.475   224.7 1142.93
   237.8 1143.78     251 1146.13   290.4 1160.32   296.9  1163.2   303.5 1167.14
   310.1 1169.53   329.7  1169.9     333 1170.41   336.3 1172.64   342.9 1179.44
   346.2 1181.75   359.3 1187.12   388.8 1194.57   408.5 1201.93   426.4 1205.81
#Mann= 4 ,-1,0
       0     .05       0  207.33    .045       0  218.04     .05       0
  282.53     .06       0
Bank Sta=207.33,218.04
XS Rating Curve= 0 ,0
Exp/Cntr(USF)=0,0
Exp/Cntr=0.3,0.1

Type RM Length L Ch R = 1 ,8744    ,399.7,404.3,408.3
XS GIS Cut Line= 2
1680290.54414234485269.3096147631680460.13529666485656.690041303
#Sta/Elev= 30
       0 1154.26    17.8 1153.61    42.8 1151.56    93.4 1148.36   107.7 1146.13
   125.6 1141.22   137.4 1139.57   187.2 1139.34   200.8 1140.47   204.4 1140.04
  207.76 1138.44   211.6 1137.01   213.5 1136.95   215.1 1137.01  220.091138.443
   225.9 1140.15   240.2 1143.11   247.4 1145.16   272.4 1156.27   290.3 1163.76
   297.5 1164.66   311.8 1164.31   315.4 1164.64   329.7 1171.88   344.2 1175.95
     362 1182.57   383.5 1191.62   408.5 1203.34   412.1 1204.07   422.9 1204.54
#Mann= 4 ,-1,0
       0     .05       0  207.76    .045       0  220.09     .05       0
     350     .06       0
Bank Sta=207.76,220.09
XS Rating Curve= 0 ,0
Exp/Cntr(USF)=0,0
Exp/Cntr=0.3,0.1

Type RM Length L Ch R = 1 ,8340    ,65.3,65.6,65.6
XS GIS Cut Line= 5
1680157.14685315485312.6199665751680000.48874937485485.093867741
1679979.19643684485553.2292678481679980.89982184485594.110507912
1680038.30941381 485744.49007117
#Sta/Elev= 30
       0 1149.11    81.5 1143.83   185.6 1138.67   220.8 1136.42     237  1135.7
   258.1 1135.66   261.5 1135.23   265.91133.428   268.4 1132.44   271.8 1131.97
   275.3 1132.54  277.921133.428   282.1 1134.78     289 1135.53   364.5 1136.42
   373.6 1137.05   377.1  1137.7   380.7 1139.14   388.4 1143.33   391.2 1144.33
   394.7 1144.97   405.2 1145.76   422.8 1145.36   426.3 1146.45   436.8 1152.33
   454.4 1159.21   461.4 1161.36   469.3 1163.27   482.5 1165.68   506.3 1168.82
#Mann= 4 ,-1,0
       0     .05       0   265.9    .045       0  277.92     .05       0
  304.38     .06       0
Bank Sta=265.9,277.92
XS Rating Curve= 0 ,0
Exp/Cntr(USF)=0,0
Exp/Cntr=0.3,0.1

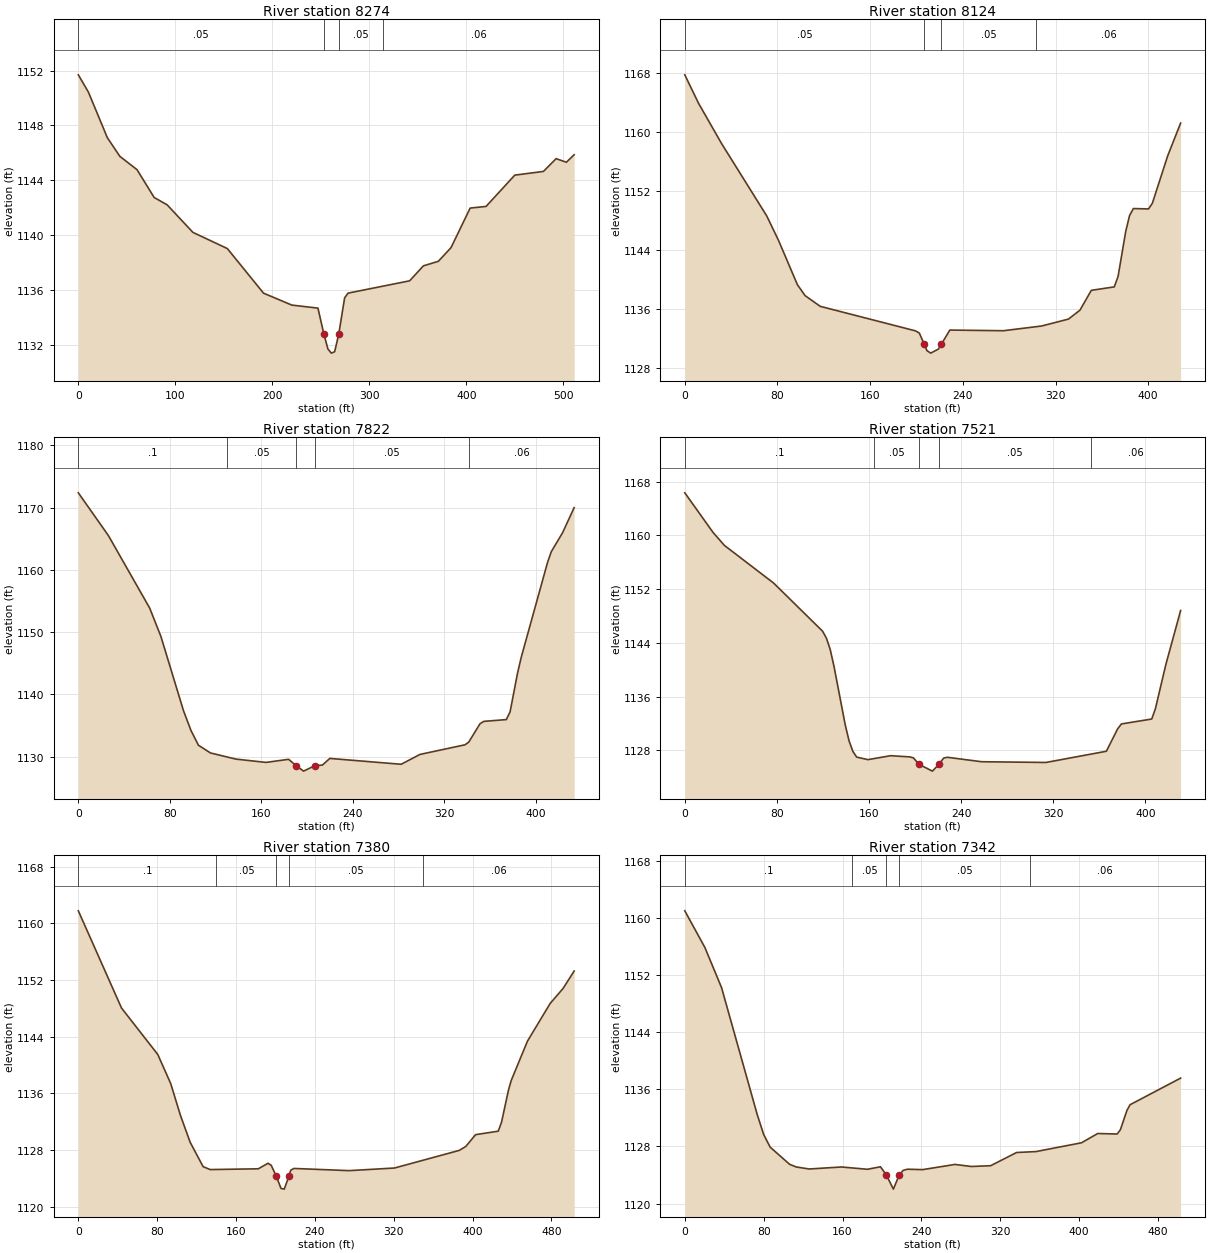
Type RM Length L Ch R = 1 ,8274    ,152.7,150.4,146.7
XS GIS Cut Line= 5
1680091.16734253485310.0400555071679934.50923875485482.513956673
1679913.21692622 485550.649356781679914.92031122485591.530596845
1679909.30465809485757.240625127
#Sta/Elev= 30
       0 1151.69    10.4 1150.43    29.9 1147.11    42.8 1145.75    60.5 1144.78
    78.2 1142.75    91.5 1142.22   118.1 1140.21   153.6 1139.03   190.9 1135.78
   220.1 1134.91     247 1134.69  253.191132.774   257.3 1131.71   260.8 1131.41
   264.2 1131.51  268.391132.774   274.5 1135.44     278 1135.78   341.5 1136.68
   355.7 1137.77   371.1  1138.1   384.2  1139.1   403.9 1141.98   420.3  1142.1
   449.9 1144.38   479.4 1144.65   492.5 1145.58   503.1 1145.32   511.1 1145.87
#Mann= 4 ,-1,0
       0     .05       0  253.19    .045       0  268.39     .05       0
  314.38     .06       0
Bank Sta=253.19,268.39
XS Rating Curve= 0 ,0
Exp/Cntr(USF)=0,0
Exp/Cntr=0.3,0.1

Type RM Length L Ch R = 1 ,8124    ,296.4,301.3,295.5
XS GIS Cut Line= 6
1679766.64164685485287.1701433361679769.50351776 485374.58302626
1679771.95626876485449.5156191741679781.78498925485550.139105588
1679790.68884283485625.7272090021679798.39584842485713.706363752
#Sta/Elev= 30
       0 1167.75    11.9 1163.88    31.6 1158.46    70.7 1148.61    80.8 1145.32
    97.2 1139.27   103.8 1137.79   116.9 1136.33   199.2    1133   202.5 1132.69
  206.641131.198     209 1130.32   212.3 1129.98   218.9 1130.53   221.5  1131.2
   228.8 1133.11     275 1133.02     308 1133.66   331.2  1134.6   341.1 1135.81
   350.9  1138.5   370.7 1138.97     374 1140.38   380.6 1146.49   383.9 1148.64
   387.2  1149.6   400.3 1149.55   403.6 1150.32   416.8 1156.74     428  1161.2
#Mann= 4 ,-1,0
       0     .05       0  206.64    .045       0   221.5     .05       0
  303.53     .06       0
Bank Sta=206.64,221.5
XS Rating Curve= 0 ,0
Exp/Cntr(USF)=0,0
Exp/Cntr=0.3,0.1

Type RM Length L Ch R = 1 ,7822    ,294.8,301.5,295.9
XS GIS Cut Line= 4
1679503.64491836485302.3113036551679504.77209184485561.277862832
1679506.59492284485643.8659522531679507.84984159485735.644640088
#Sta/Elev= 30
       0 1172.37    26.3  1165.5    62.4 1153.85    72.2 1149.29    91.9 1137.39
    98.5 1134.18     105 1131.83   115.5 1130.59   137.8  1129.6   164.1 1129.07
   183.8 1129.57  190.481128.533   196.9 1127.67   206.7 1128.54   213.3 1128.64
   219.8 1129.71   282.2 1128.77   298.6 1130.35     338  1131.9   341.3 1132.34
   351.1 1135.28   354.4 1135.66   374.1 1135.95   377.4 1137.19   383.9  1143.4
   387.2 1145.99   410.2 1161.23   413.4 1162.91   423.3 1165.97   433.4 1169.99
#Mann= 5 ,-1,0
       0      .1       0     130     .05       0  190.48    .045       0
   206.7     .05       0  341.58     .06       0
Bank Sta=190.48,206.7
XS Rating Curve= 0 ,0
Exp/Cntr(USF)=0,0
Exp/Cntr=0.3,0.1

Type RM Length L Ch R = 1 ,7521    ,132.2,140.6,135.9
XS GIS Cut Line= 6
1679238.68830642485330.2615925821679238.54788676485418.462203592
1679239.82413092485494.5870513321679248.38940251485596.351611584
1679250.65416175485672.2979820071679251.77292593485760.543540418
#Sta/Elev= 30
       0 1166.34    24.6 1160.43    34.4 1158.51    77.1 1152.91   119.7 1145.73
     123  1144.7   126.3 1143.02   129.6  1140.5   139.4 1131.75   142.7 1129.39
     146 1127.83   149.3 1126.98   159.1  1126.6   178.8 1127.19   195.3 1127.01
   198.6 1126.87  203.361125.907   215.1 1124.89  220.751125.905   224.9 1126.84
   228.2 1126.95   257.8 1126.29   313.7 1126.18   366.2 1127.85     376 1131.19
   379.3 1131.92   405.6 1132.65   408.8 1134.19   417.9 1140.79   430.7 1148.81
#Mann= 5 ,-1,0
       0      .1       0  164.34     .05       0  203.36    .045       0
  220.75     .05       0  352.44     .06       0
Bank Sta=203.36,220.75
XS Rating Curve= 0 ,0
Exp/Cntr(USF)=0,0
Exp/Cntr=0.3,0.1

Type RM Length L Ch R = 1 ,7380    ,38.5,38.5,38.5
XS GIS Cut Line= 2
1679110.47008547485356.4883000391679147.09286303485858.135183327
#Sta/Elev= 30
       0 1161.78    43.8 1148.06    80.6  1141.5    93.7  1137.4   103.6  1132.9
   113.5 1129.09   126.6 1125.66   133.8 1125.25   182.6 1125.36   192.4 1126.14
   195.7 1125.85  200.861124.291   205.6 1122.59   208.9 1122.49  213.56 1124.29
   215.5 1125.16   218.7 1125.41   274.7  1125.1   320.7 1125.47   386.5 1127.96
   393.1 1128.52     403 1130.18     426 1130.67   429.3 1131.92   436.2 1136.37
   439.1 1137.81   455.6 1143.37   478.6 1148.69   491.8 1150.83     503 1153.28
#Mann= 5 ,-1,0
       0      .1       0     140     .05       0  200.86    .045       0
  213.56     .05       0     350     .06       0
Bank Sta=200.86,213.56
XS Rating Curve= 0 ,0
Exp/Cntr(USF)=0,0
Exp/Cntr=0.3,0.1

Type RM Length L Ch R = 1 ,7342    ,190.6,191.8,190.7
XS GIS Cut Line= 2
1679072.56976916485360.3209162951679109.19254672485861.967799583
#Sta/Elev= 30
       0    1161    20.4 1155.86    37.3 1150.24    73.4  1132.5      80 1129.68
    86.6  1127.9   106.3  1125.5   112.9 1125.13   126.1 1124.84     159 1125.12
   185.3  1124.8   198.5 1125.15  204.531123.988   211.6 1122.02   217.51123.989
   221.5 1124.64   225.8 1124.81   241.3 1124.75   274.1 1125.48   290.6 1125.19
   310.3  1125.3   336.6 1127.15   356.3 1127.28   402.4 1128.51   418.9 1129.81
   438.6 1129.74   441.9 1130.34   448.5 1133.03   451.7 1133.84     503 1137.57
#Mann= 5 ,-1,0
       0      .1       0     170     .05       0  204.53    .045       0
   217.5     .05       0     350     .06       0
Bank Sta=204.53,217.5
XS Rating Curve= 0 ,0
Exp/Cntr(USF)=0,0
Exp/Cntr=0.3,0.1

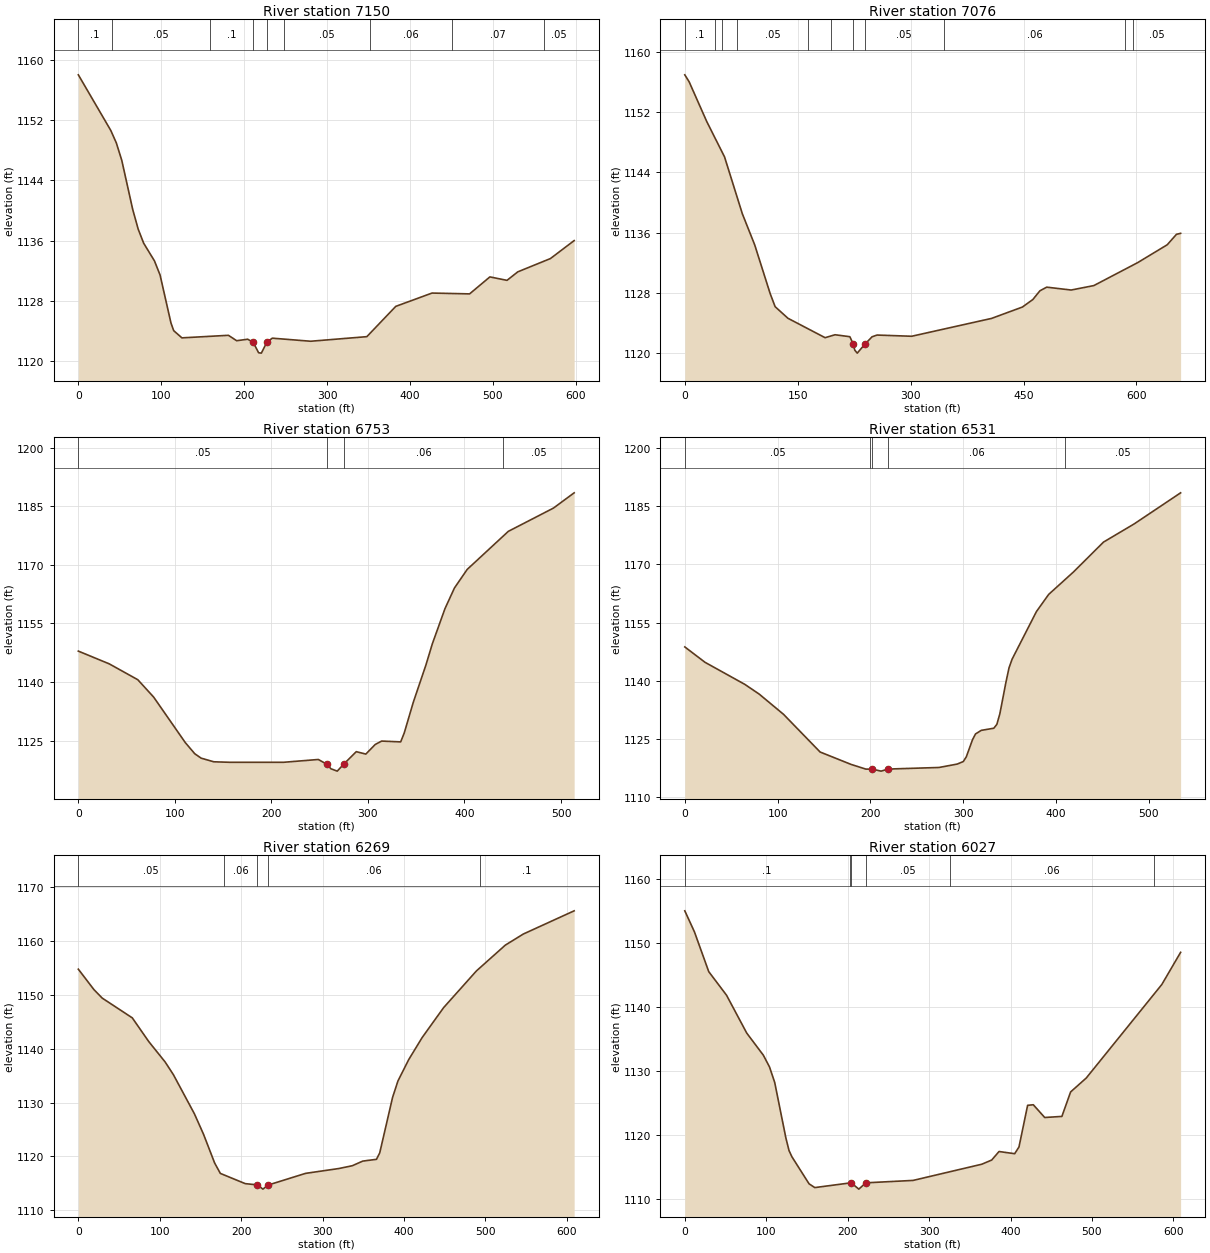
Type RM Length L Ch R = 1 ,7150    ,71.2,73.4,71.5
XS GIS Cut Line= 4
1678884.65984919485397.809022843 1678898.7966144485545.394058225
1678915.62176767485687.3235205591679078.43277416485947.295713155
#Sta/Elev= 30
       0 1158.05    39.2 1150.64    45.8    1149    52.4 1146.67    65.6 1140.13
    72.2 1137.52    78.8 1135.65    91.8  1133.3    98.6 1131.41   111.7 1125.04
     115 1124.02   124.9 1123.06     181  1123.4   190.9 1122.68   204.2 1122.88
  210.841122.471   217.4 1121.08   220.7 1121.03   227.3 1122.47   233.9 1123.02
   280.1 1122.61   347.9 1123.22   382.8 1127.25   426.5 1129.02   471.8 1128.91
   496.3 1131.17   516.9 1130.71   529.9 1131.84   569.3 1133.61   597.9    1136
#Mann= 9 ,-1,0
       0      .1       0      40     .05       0  158.26      .1       0
  210.84    .045       0   227.3      .1       0  248.26     .05       0
  351.18     .06       0  451.18     .07       0  561.18     .05       0
Bank Sta=210.84,227.3
XS Rating Curve= 0 ,0
Exp/Cntr(USF)=0,0
Exp/Cntr=0.3,0.1

Type RM Length L Ch R = 1 ,7076    ,313.2,323.7,312.8
XS GIS Cut Line= 4
1678871.17047253485398.5254966771678838.78017755485538.750495325
1678848.84276673485749.6442792681679067.85948047485960.034019415
#Sta/Elev= 30
       0 1156.97     5.7 1156.06    29.2 1150.76    52.8 1146.07    76.4 1138.53
    92.9 1134.38   113.4 1127.92     120 1126.18     137 1124.64   186.4 1122.06
   199.6 1122.45   219.3 1122.19  223.821121.195   225.8 1120.41   229.1 1120.01
  239.221121.193   248.8 1122.18   255.4 1122.41   301.4 1122.25   407.5 1124.62
   448.5 1126.13   462.4 1127.13   471.8 1128.29   480.8 1128.77   513.3 1128.39
   543.4 1128.98   601.5 1132.02   640.9  1134.4   653.2 1135.79   658.7 1135.92
#Mann= 11 ,-1,0
       0      .1       0      40     .05       0      50      .1       0
      70     .05       0  163.92      .1       0  193.92     .05       0
  223.82    .045       0  239.22     .05       0  343.92     .06       0
  585.05     .07       0  595.05     .05       0
Bank Sta=223.82,239.22
XS Rating Curve= 0 ,0
Exp/Cntr(USF)=0,0
Exp/Cntr=0.3,0.1

Type RM Length L Ch R = 1 ,6753    ,218.4,222,219.4
XS GIS Cut Line= 2
1678617.28246481485444.194590364 1678618.5226288485957.770170509
#Sta/Elev= 30
       0 1147.92      32 1144.66    61.6  1140.6      78 1136.16   110.8 1124.51
   120.6 1121.66   127.2 1120.53   140.3  1119.6   156.7 1119.47   212.5 1119.47
   248.6 1120.19  257.171119.003   261.7 1117.81   268.2 1117.21  274.951119.005
   287.9 1122.19   297.8 1121.57   307.6 1124.04   314.2  1124.9   333.9 1124.69
   337.6 1126.98     347 1134.85   360.1  1144.4   366.7 1149.79   379.8 1158.79
   389.6 1164.07   402.8 1168.82   445.4 1178.56   492.2 1184.52   513.6 1188.42
#Mann= 4 ,-1,0
       0     .05       0  257.17    .045       0  274.95     .06       0
     440     .05       0
Bank Sta=257.17,274.95
XS Rating Curve= 0 ,0
Exp/Cntr(USF)=0,0
Exp/Cntr=0.3,0.1

Type RM Length L Ch R = 1 ,6531    ,256.6,261.9,261.8
XS GIS Cut Line= 2
1678437.29261338485422.3948090781678415.69933061485956.228744027
#Sta/Elev= 30
       0 1148.71    21.8 1144.74    64.5 1139.08    80.1 1136.56   106.4 1131.33
   145.8 1121.62   179.2 1118.42   195.1 1117.21   201.91117.204   211.5 1116.69
   219.11117.223   273.9 1117.63   293.6 1118.51   300.1 1119.16   303.4  1120.4
     310 1124.77   313.3 1126.28   319.5  1127.2     333 1127.75   336.3 1128.76
   339.5 1131.47   346.1 1139.65   349.4 1143.33   352.7 1145.55   378.9 1157.81
   392.1 1162.24   418.8 1168.02   451.2 1175.73   484.2 1180.41   534.3 1188.43
#Mann= 5 ,-1,0
       0     .05       0     200     .06       0   201.9    .045       0
   219.1     .06       0     410     .05       0
Bank Sta=201.9,219.1
XS Rating Curve= 0 ,0
Exp/Cntr(USF)=0,0
Exp/Cntr=0.3,0.1

Type RM Length L Ch R = 1 ,6269    ,241.2,241.4,238.6
XS GIS Cut Line= 4
1678251.34259236485382.0823079991678215.88178047485537.230263543
1678166.73484719485673.2981949041678200.27107732485976.798070229
#Sta/Elev= 30
       0  1154.8    19.2    1151    29.3 1149.43    66.3 1145.75    86.5 1141.35
   106.7 1137.54   116.8 1135.19   142.6 1127.92   153.8 1124.12   167.5 1118.76
   174.5 1116.83   205.1 1114.93   219.9  1114.7   226.8 1113.91   233.3 1114.67
   279.2 1116.84   320.1 1117.74   336.6 1118.26   349.5 1119.12   366.3 1119.45
   370.3 1120.64   386.1 1130.96   392.7 1134.02   405.9 1137.98   422.4 1142.08
   448.8 1147.65   489.2 1154.49   524.7 1159.28   546.8 1161.34   609.2 1165.65
#Mann= 5 ,-1,0
       0     .05       0  179.15     .06       0   219.9    .045       0
   233.3     .06       0  493.82      .1       0
Bank Sta=219.9,233.3
XS Rating Curve= 0 ,0
Exp/Cntr(USF)=0,0
Exp/Cntr=0.3,0.1

Type RM Length L Ch R = 1 ,6027    ,293.5,298.5,297.6
XS GIS Cut Line= 6
1678055.52991159485307.7350628381678023.81573617 485389.28542468
1677996.63206351485459.1855473371677973.07928909485559.963889092
1677960.94447084485639.6093990951677867.87391489485884.869118856
#Sta/Elev= 30
       0 1155.04    11.8 1151.77    29.4 1145.55    51.3 1141.86    76.1 1135.95
    96.5  1132.5     104 1130.68   110.4 1128.26   124.2 1119.55     128 1117.62
   131.5 1116.66   152.6 1112.43   159.7 1111.84  204.28 1112.59   213.7  1111.6
  222.321112.582   280.4 1112.96   364.8 1115.49   376.9 1116.14   385.9 1117.47
   405.1 1117.13   410.4 1118.18     421 1124.68     428 1124.77     442 1122.78
   463.1 1122.95   473.8 1126.77     493 1128.94   585.8 1143.54   608.9 1148.56
#Mann= 6 ,-1,0
       0      .1       0   202.5     .05       0  204.28    .045       0
  222.32     .05       0  325.99     .06       0  576.56      .1       0
Bank Sta=204.28,222.32
XS Rating Curve= 0 ,0
Exp/Cntr(USF)=0,0
Exp/Cntr=0.3,0.1

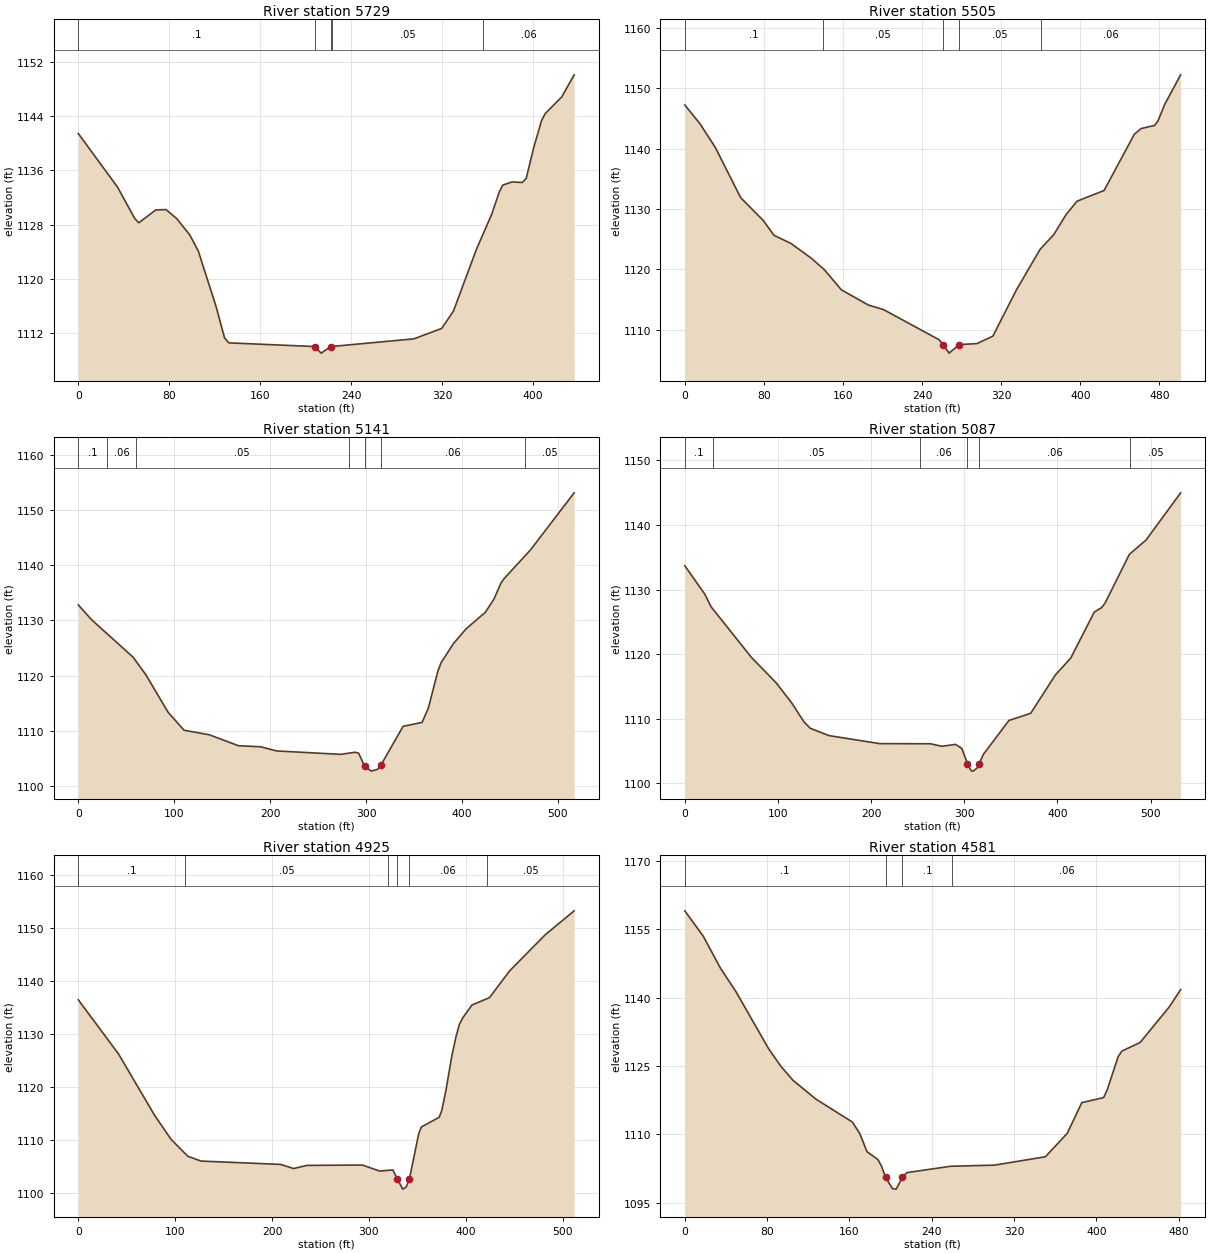
Type RM Length L Ch R = 1 ,5729    ,224.3,224,220.2
XS GIS Cut Line= 6
1677832.74886109485241.9287640011677792.47597575485320.149736166
1677753.34022726485384.5032820111677702.52635251 485473.99982217
1677682.07002859485550.6561649291677661.38076551485638.732432336
#Sta/Elev= 30
       0 1141.41    34.5 1133.52    49.5 1128.93    53.2 1128.27      68 1130.16
    77.1 1130.22    86.4 1128.91    97.9 1126.51   105.5 1124.11   120.9 1116.06
   128.6 1111.31   132.4 1110.59   207.8 1110.05   213.5 1109.08   222.11110.048
     295 1111.18   319.5 1112.71   329.9 1115.28     350 1124.34   363.5 1129.53
   370.2 1132.83   373.2 1133.82   381.4 1134.29   390.4 1134.21   393.8 1134.79
   400.5 1139.38   407.3 1143.31   410.6 1144.36   425.1 1146.81     436 1150.06
#Mann= 5 ,-1,0
       0      .1       0   207.8    .045       0   222.1      .1       0
   223.3     .05       0  355.55     .06       0
Bank Sta=207.8,222.1
XS Rating Curve= 0 ,0
Exp/Cntr(USF)=0,0
Exp/Cntr=0.3,0.1

Type RM Length L Ch R = 1 ,5505    ,362.2,367.3,363.2
XS GIS Cut Line= 2
1677608.91400313485100.7080789891677473.51467143485583.632148832
#Sta/Elev= 30
       0 1147.25    15.2 1144.18    30.8 1140.24    56.5  1131.9    79.4 1128.11
    90.2 1125.66   107.2 1124.33     128 1121.86   141.3 1119.94   158.3 1116.64
   185.6 1114.11   200.9 1113.36   257.1 1108.37  261.391107.553   267.3 1106.14
  277.651107.553   295.4 1107.72   311.6 1108.95   335.3 1116.58   359.3 1123.32
     373 1125.73   385.8 1129.12   396.8 1131.32   424.1 1133.09   454.7 1142.41
   461.6 1143.35   475.2 1143.87   478.6 1144.61   485.4 1147.35   501.5 1152.25
#Mann= 5 ,-1,0
       0      .1       0     140     .05       0  261.39    .045       0
  277.65     .05       0     360     .06       0
Bank Sta=261.39,277.65
XS Rating Curve= 0 ,0
Exp/Cntr(USF)=0,0
Exp/Cntr=0.3,0.1

Type RM Length L Ch R = 1 ,5141    ,52.1,51.6,51.1
XS GIS Cut Line= 5
1677272.26256915485108.2879459851677236.41079654485317.165992732
1677198.15894393 485386.586021551677190.04424529485440.471139771
1677205.47074119485611.189644607
#Sta/Elev= 30
       0 1132.81    13.8 1130.13    57.1 1123.34    70.4 1120.16    93.7 1113.33
   110.3 1110.09   136.6 1109.27   166.9 1107.29   190.2 1107.09   206.9 1106.34
   273.5 1105.72   288.7  1106.1   292.3 1105.94298.58151103.572   305.5 1102.68
   312.2 1103.02   315.5 1103.75   338.7  1110.8   358.5 1111.51   365.1 1114.14
     375 1120.83   378.3 1122.32   391.1 1125.78   404.6 1128.51   424.4 1131.46
   433.4 1133.85   440.9 1136.81   444.2 1137.61   471.6 1142.79   517.1 1153.13
#Mann= 7 ,-1,0
       0      .1       0      30     .06       0      60     .05       0
  281.93     .06       0298.5815    .045       0   315.5     .06       0
  465.69     .05       0
Bank Sta=298.5815,315.5
XS Rating Curve= 0 ,0
Exp/Cntr(USF)=0,0
Exp/Cntr=0.3,0.1

Type RM Length L Ch R = 1 ,5087    ,260.1,263.8,266.8
XS GIS Cut Line= 5
1677232.62792926485103.9342267981677198.86731157485303.707007553
1677149.98994434485366.0433599611677131.98840486 485439.95416517
1677154.49857718485612.797772929
#Sta/Elev= 30
       0 1133.69    21.5 1129.28    28.2 1127.33    71.5 1119.49    98.1 1115.54
   114.7 1112.44     128 1109.48   134.7  1108.5   154.6 1107.37   209.2 1106.12
   263.7  1106.1   275.9 1105.71   290.6    1106   297.3 1105.39303.40531103.039
   307.4 1101.91   309.6 1101.86   314.2 1102.41315.74051102.953   320.5 1104.46
   347.9 1109.71   371.3 1110.82   397.8 1116.77   414.3 1119.39   439.5  1126.5
   447.4  1127.2   451.2 1127.93   477.2 1135.46   495.2 1137.69   532.2 1144.99
#Mann= 6 ,-1,0
       0      .1       0      30     .05       0  252.61     .06       0
303.4053    .045       0315.7405     .06       0  477.89     .05       0
Bank Sta=303.4053,315.7405
XS Rating Curve= 0 ,0
Exp/Cntr(USF)=0,0
Exp/Cntr=0.3,0.1

Type RM Length L Ch R = 1 ,4925    ,305,307.2,305.2
XS GIS Cut Line= 3
 1677100.8816729485065.9747879971676997.30119097485422.878203892
1676952.54675211485555.728065888
#Sta/Elev= 30
       0 1136.45    41.6  1126.2    78.7 1114.65    95.8 1110.08   113.1  1106.9
   126.6    1106   208.7 1105.37   222.2 1104.59   235.9 1105.18   293.2 1105.25
     311 1104.11   324.7 1104.33   329.41102.562   334.9  1100.7   338.4 1101.09
   341.8 1102.67   351.4  1111.2   354.1 1112.44   372.5 1114.27   375.2 1115.57
   379.5 1119.41   385.5 1125.81   389.8 1129.46   393.3 1131.82   396.8 1133.04
   406.3 1135.47   424.4 1136.86   445.2 1141.92     482 1148.75   511.8 1153.26
#Mann= 6 ,-1,0
       0      .1       0     110     .05       0     320     .06       0
   329.4    .045       0   341.8     .06       0  421.63     .05       0
Bank Sta=329.4,341.8
XS Rating Curve= 0 ,0
Exp/Cntr(USF)=0,0
Exp/Cntr=0.3,0.1

Type RM Length L Ch R = 1 ,4581    ,251.5,252,250.4
XS GIS Cut Line= 2
1676894.05059395484983.9358619551676713.89783586485430.819645356
#Sta/Elev= 30
       0 1159.04    17.9 1153.49    34.5 1146.52    49.7 1141.32    81.5 1128.77
    93.4 1124.93   105.1 1121.87   127.5 1117.72   162.9  1112.7     170 1110.19
   177.1 1106.19   187.7 1104.47   191.2 1103.01   195.1 1100.57   201.8 1098.09
   205.4 1097.99   211.41100.543     216 1101.62   258.4 1103.01   300.9 1103.25
   350.4 1105.09   371.6 1110.22   385.8 1116.96     407 1118.07   410.5 1119.79
   421.1 1127.06   424.7 1128.27   442.4 1130.15   470.7 1137.94   481.8 1141.76
#Mann= 4 ,-1,0
       0      .1       0   195.1    .045       0   211.4      .1       0
     260     .06       0
Bank Sta=195.1,211.4
XS Rating Curve= 0 ,0
Exp/Cntr(USF)=0,0
Exp/Cntr=0.3,0.1