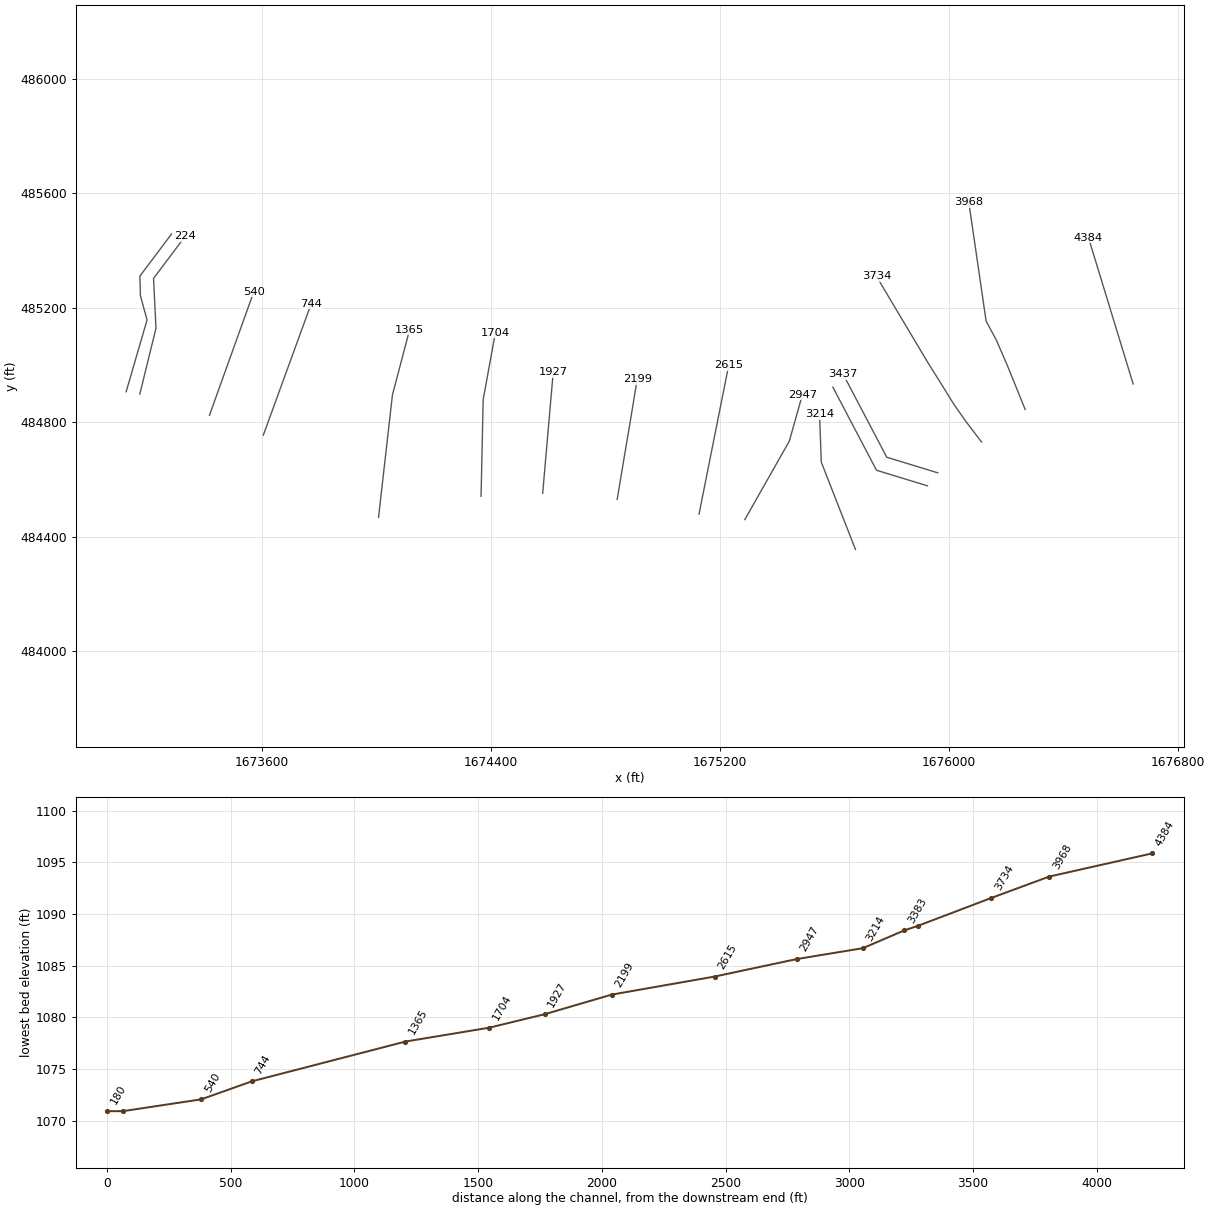
HEC-RAS study GraveCk2.prj: GraveCk2

--- GraveCk2.g01 (geometry) --- (continued)

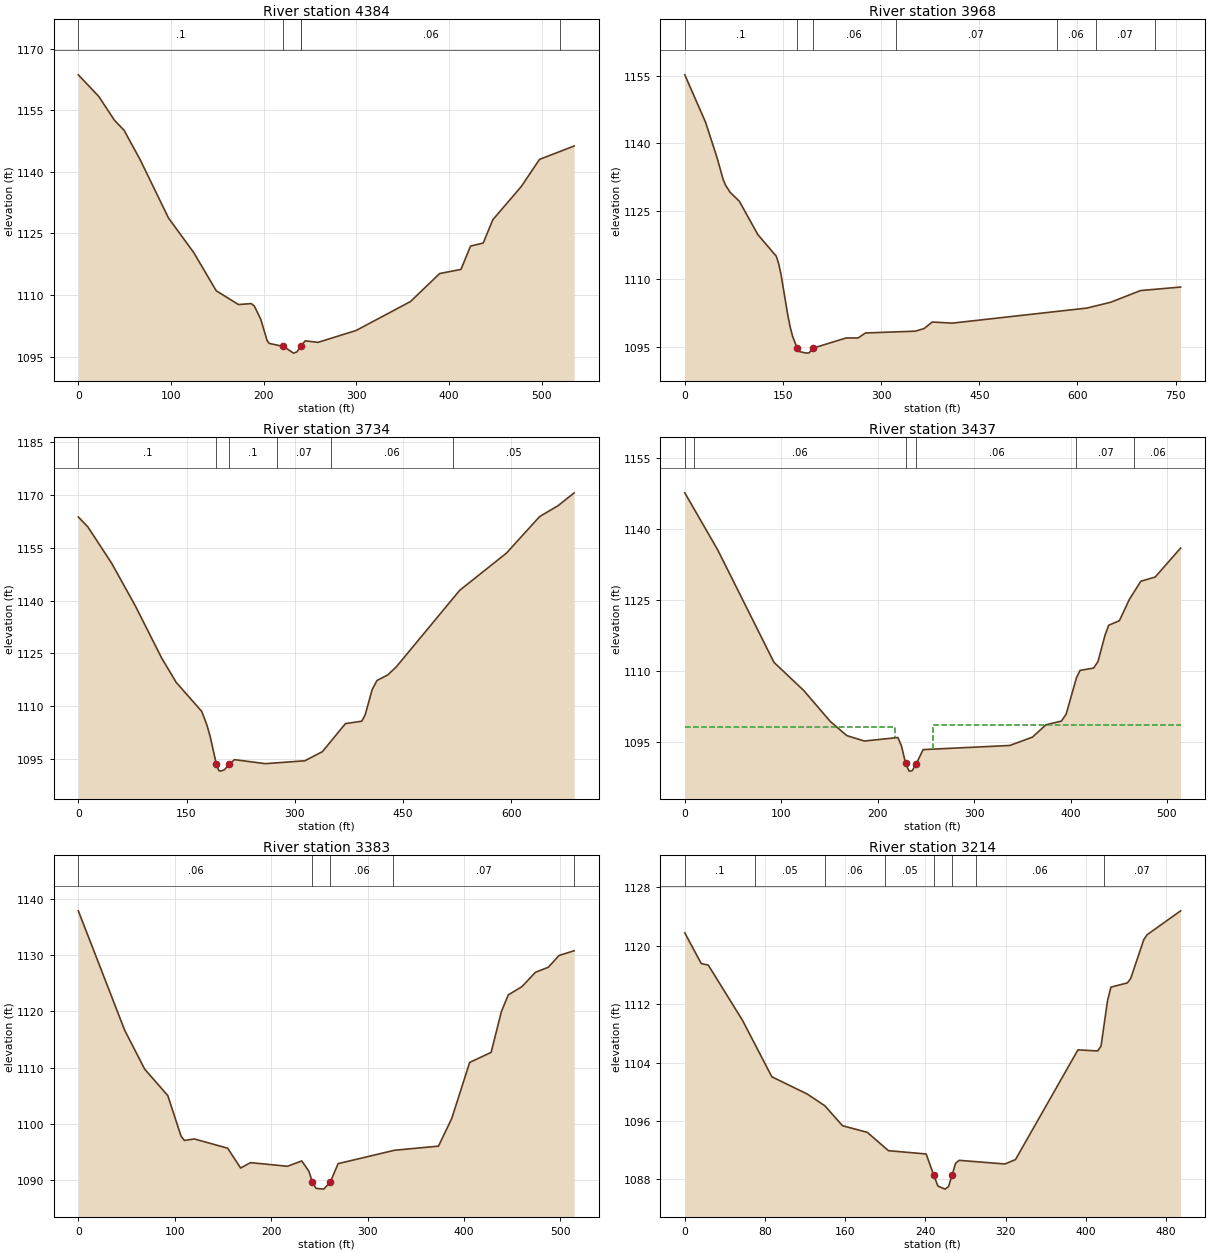
Type RM Length L Ch R = 1 ,4384    ,412.4,416,415.8
XS GIS Cut Line= 2
1676642.60685052484933.692069552 1676486.3618627485445.344780164
#Sta/Elev= 30
       0 1163.61      22 1158.37      39 1152.54    49.3 1150.13    66.7 1142.95
    97.3 1128.75   124.5 1120.35   148.8 1111.03   172.8 1107.68   186.5 1107.91
   189.9 1107.32   196.8 1104.12   203.6 1098.98   205.9 1098.22  221.361097.476
   232.2 1095.85   235.9 1096.15  239.721097.475   244.8 1098.84   258.6 1098.47
   299.7 1101.36   358.4 1108.41   389.9 1115.23   412.9 1116.24   423.2 1121.91
   436.9 1122.66   447.2 1128.32   478.1 1136.46   497.6 1143.02     535 1146.28
#Mann= 5 ,-1,0
       0      .1       0  221.36    .045       0  239.72      .1       0
     240     .06       0     520     .05       0
Bank Sta=221.36,239.72
XS Rating Curve= 0 ,0
Exp/Cntr(USF)=0,0
Exp/Cntr=0.3,0.1

Type RM Length L Ch R = 1 ,3968    ,232.1,234.4,235.4
XS GIS Cut Line= 6
1676265.46384005484844.5279420811676232.65517863484925.644249667
1676204.53285956484995.1719977451676164.80163981485086.972011004
1676129.01365363485153.5069829121676068.57368085485568.743433353
#Sta/Elev= 30
       0 1155.18    31.7 1144.71    49.4  1136.8    58.5 1132.07      62 1130.85
    69.2  1129.2    83.3 1127.22   111.6 1119.84   139.9 1115.03   143.5 1113.37
     147 1111.04   157.6 1101.86   161.2 1099.29   164.7 1097.36  171.711094.688
   175.5 1093.93   186.2 1093.61   190.2  1093.7  195.451094.689     247 1096.98
   264.8 1096.96   276.1 1098.07   352.6 1098.47   365.8 1099.06   378.1 1100.49
   408.9 1100.25   614.5 1103.58   650.9 1104.87   696.4 1107.45   757.7 1108.23
#Mann= 7 ,-1,0
       0      .1       0  171.71    .045       0  195.45     .06       0
  322.53     .07       0  568.08     .06       0  628.08     .07       0
  718.08     .06       0
Bank Sta=171.71,195.45
XS Rating Curve= 0 ,0
Exp/Cntr(USF)=0,0
Exp/Cntr=0.3,0.1

Type RM Length L Ch R = 1 ,3734    ,296.9,296.9,296.8
XS GIS Cut Line= 6
1676113.25471397484730.828011372 1676059.3233914484801.388565787
1676015.75294048484863.701433294 1675963.0361824484948.678297453
1675923.28593381485012.2779077971675745.49670312485310.842920477
#Sta/Elev= 30
       0 1163.73    13.2 1160.92    46.2 1150.59    79.2 1138.41   115.6 1123.63
   135.6 1116.77   171.1 1108.49   178.3 1104.59     183 1101.18   191.41093.426
   194.6 1091.75   197.3 1091.54   202.3  1091.9  209.161093.428   216.4  1094.8
   259.3 1093.66     314 1094.48   338.3 1097.07   370.3 1105.04   392.9 1105.72
   397.7 1107.57   407.2 1114.65     414 1117.29   428.8 1118.85   440.7 1121.14
   528.5 1142.87   593.4 1153.46   639.4 1163.84   665.3 1166.98   687.3 1170.59
#Mann= 6 ,-1,0
       0      .1       0   191.4    .045       0  209.16      .1       0
  274.85     .07       0  349.85     .06       0  519.85     .05       0
Bank Sta=191.4,209.16
XS Rating Curve= 0 ,0
Exp/Cntr(USF)=0,0
Exp/Cntr=0.3,0.1

Type RM Length L Ch R = 1 ,3437    ,54.7,54,53.5
XS GIS Cut Line= 3
1675960.05952302484623.1810563861675782.05579024484677.689376472
 1675629.6028325484968.116519428
#Sta/Elev= 30
       0 1147.56    34.2 1135.49    92.5 1111.79   123.4 1105.84   150.8 1099.34
     168 1096.34   186.2 1095.19     221 1095.93   224.7 1094.15  229.07 1090.45
   232.6 1088.84   235.8 1088.92  240.221090.447   247.1 1093.38     337 1094.25
   360.5 1096.01   374.6 1098.63   390.5 1099.39   395.4 1100.82   406.2 1108.55
   409.9 1110.09     424 1110.59   428.5 1111.96   435.9  1117.6   439.6 1119.62
   450.7 1120.58     461 1125.06   472.9  1128.9   487.8 1129.79   514.2 1135.91
#Mann= 6 ,-1,0
       0      .1       0      10     .06       0  229.07    .045       0
  240.22     .06       0  406.16     .07       0  466.16     .06       0
#XS Ineff= 2 , 0
          218.34 1098.09  257.33         1098.48
Permanent Ineff=
       F       F
Bank Sta=229.07,240.22
XS Rating Curve= 0 ,0
Exp/Cntr(USF)=0,0
Exp/Cntr=0.3,0.1

Type RM Length L Ch R = 1 ,3383    ,169.3,168.7,167.3
XS GIS Cut Line= 3
1675924.28843797484577.6155075641675746.28470519 484632.12382765
1675593.83174745484922.550970607
#Sta/Elev= 30
       0 1137.87    48.2  1116.6    68.8 1109.74    92.8 1105.03   106.5 1097.84
     110 1097.06   120.3 1097.33   154.9 1095.68   168.3 1092.16   178.6 1093.12
   216.9 1092.47   231.7 1093.42   239.1 1091.59  242.741089.651   246.5 1088.55
   254.4 1088.41  261.271089.649   269.4 1092.94     328 1095.32   373.5 1096.05
   387.3 1100.99   405.8 1110.92   428.1 1112.72   438.8    1120   445.9 1122.93
     460 1124.39   474.1 1126.95   487.4 1127.84   498.5 1129.93   514.2 1130.78
#Mann= 5 ,-1,0
       0     .06       0  242.74    .045       0  261.27     .06       0
  326.16     .07       0  514.17     .06       0
Bank Sta=242.74,261.27
XS Rating Curve= 0 ,0
Exp/Cntr(USF)=0,0
Exp/Cntr=0.3,0.1

Type RM Length L Ch R = 1 ,3214    ,273.9,266.8,257.4
XS GIS Cut Line= 3
1675672.78350632484355.3473453941675553.39593951484660.494688656
 1675547.4204265484827.213714167
#Sta/Elev= 30
       0 1121.73    16.4 1117.54    23.4 1117.33    57.6 1109.76    86.8 1102.05
   122.1 1099.69   139.7 1098.08   157.3 1095.35     182 1094.45   203.1 1091.94
   240.7 1091.49  248.121088.657   252.4 1087.11   259.5 1086.68     263 1087.03
  266.691088.657     270  1090.2   273.6 1090.62   319.3 1090.12   329.8 1090.72
   392.1 1105.73   411.8 1105.58   415.1 1106.23   421.6 1112.46     425 1114.31
   441.4 1114.89   444.7 1115.49   457.8 1120.82   461.1 1121.48   494.5 1124.75
#Mann= 8 ,-1,0
       0      .1       0      70     .05       0     140     .06       0
     200     .05       0  248.12    .045       0  266.69     .05       0
     290     .06       0  417.67     .07       0
Bank Sta=248.12,266.69
XS Rating Curve= 0 ,0
Exp/Cntr(USF)=0,0
Exp/Cntr=0.3,0.1

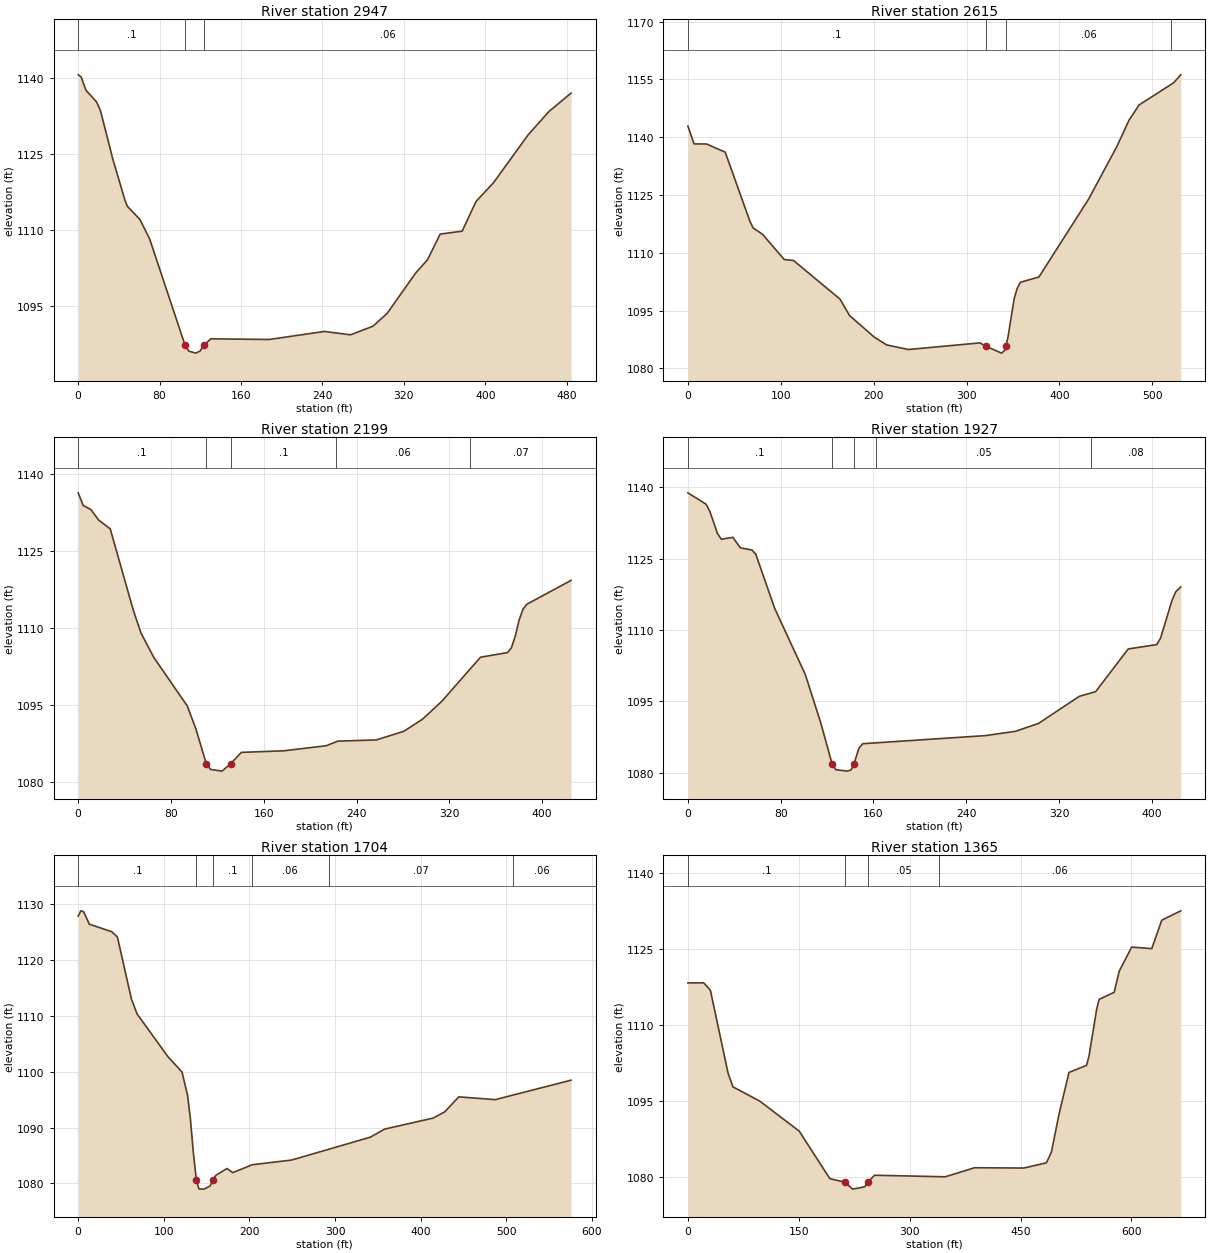
Type RM Length L Ch R = 1 ,2947    ,322.9,331.8,332.4
XS GIS Cut Line= 3
1675286.40457565484459.844564637 1675441.7078934484733.742640443
1675487.61884188484896.843888878
#Sta/Elev= 30
       0 1140.69       3 1140.25     7.6 1137.64    18.1 1135.32    21.9 1133.59
    34.1 1123.97    46.1 1115.79    48.3 1114.69    60.6 1112.09    70.2 1108.24
  104.931087.241   108.7 1086.03   115.6 1085.63   119.9 1086.06  123.51 1087.24
   130.4 1088.46   187.8 1088.33     242 1089.92   267.6 1089.25   289.6 1090.95
   303.7 1093.52   331.8 1101.53   343.2 1104.09   355.7 1109.18   377.3 1109.76
   390.9 1115.63     408 1119.32     442 1128.79   462.5 1133.42   484.3 1137.08
#Mann= 3 ,-1,0
       0      .1       0  104.93    .045       0  123.51     .06       0
Bank Sta=104.93,123.51
XS Rating Curve= 0 ,0
Exp/Cntr(USF)=0,0
Exp/Cntr=0.3,0.1

Type RM Length L Ch R = 1 ,2615    ,412.1,416.7,414.2
XS GIS Cut Line= 2
1675126.44521859484478.8400670891675230.11255566484999.305093965
#Sta/Elev= 30
       0 1142.87     6.7 1138.26    20.1 1138.23    40.2 1136.11    66.9 1118.09
    70.3 1116.43    80.3 1114.81   103.7 1108.25   113.8 1107.98   163.9 1097.94
     174 1093.72   200.7 1088.09   214.1 1086.06   237.5 1084.88   314.5  1086.6
  320.591085.765   337.8 1083.94   341.2 1084.66  342.321085.751   344.6 1088.01
   351.3 1098.08   354.6 1100.75     358 1102.33     378 1103.71   431.6 1123.98
   461.7  1137.5     475 1144.42   485.8 1148.36   522.9 1154.11   530.7 1156.19
#Mann= 4 ,-1,0
       0      .1       0  320.59    .045       0  342.32     .06       0
     520     .05       0
Bank Sta=320.59,342.32
XS Rating Curve= 0 ,0
Exp/Cntr(USF)=0,0
Exp/Cntr=0.3,0.1

Type RM Length L Ch R = 1 ,2199    ,270.5,271.4,272.1
XS GIS Cut Line= 6
1674840.63848041484530.3804635291674854.95144392484616.738230456
1674867.36513299484690.7311926971674884.08229116484789.325155619
1674896.23121699484863.307947282 1674910.4040889484949.616173614
#Sta/Elev= 30
       0  1136.4     4.3 1133.95      11 1133.13    17.6  1131.1    27.6  1129.4
    47.5 1113.56    54.2 1109.07    65.2 1104.34    94.1 1094.87   101.4 1090.48
  110.471083.631   114.1 1082.52     124 1082.19   131.51083.632   140.7 1085.84
   177.3 1086.15   213.9 1087.14   223.9 1088.03   257.1 1088.27   280.8 1089.95
     297 1092.32   313.7 1095.83   346.9 1104.38   370.2 1105.28   373.5 1106.19
   376.8 1108.41   380.2 1111.61   383.5  1113.7   386.8 1114.69     425 1119.34
#Mann= 5 ,-1,0
       0      .1       0  110.47    .045       0   131.5      .1       0
  222.56     .06       0  337.54     .07       0
Bank Sta=110.47,131.5
XS Rating Curve= 0 ,0
Exp/Cntr(USF)=0,0
Exp/Cntr=0.3,0.1

Type RM Length L Ch R = 1 ,1927    ,223.2,223.8,224.4
XS GIS Cut Line= 6
1674580.42834918484551.8349717191674588.00904267484639.006057225
1674594.50607693 484713.724083641674603.16944543484813.348228224
1674609.66680776484888.0659265441674617.24618893484975.237012051
#Sta/Elev= 30
       0 1138.86    15.7 1136.47      19 1134.91    25.5 1130.31    28.8 1129.09
    38.7  1129.5    45.3 1127.28    55.2 1126.83    58.5 1125.97    74.9 1114.51
   101.3 1100.59   114.5 1090.51   124.3 1081.85   127.6 1080.59   137.5 1080.29
   140.8 1080.56  143.291081.854   147.4 1085.08   150.7 1086.06   256.8 1087.77
   282.4 1088.67   302.2 1090.31   337.5 1096.03   351.6 1097.02   379.7    1106
   404.3 1106.92   407.6 1108.29   417.4  1116.2   420.7 1118.04     425 1119.07
#Mann= 5 ,-1,0
       0      .1       0   124.3    .045       0  143.29      .1       0
   162.5     .05       0   347.5     .08       0
Bank Sta=124.3,143.29
XS Rating Curve= 0 ,0
Exp/Cntr(USF)=0,0
Exp/Cntr=0.3,0.1

Type RM Length L Ch R = 1 ,1704    ,339.1,338.2,335.6
XS GIS Cut Line= 6
 1674365.2186818484541.3513597921674367.12025279 484628.83084362
1674368.75049887484703.8129771281674370.92372288484803.789483212
1674372.55396895484878.7719447831674415.24214496485113.103267562
#Sta/Elev= 30
       0 1127.83     3.1 1128.78     6.4 1128.61      13  1126.4    39.2 1125.04
    45.8 1124.09    62.2    1113    68.8 1110.33   104.9 1102.68   121.3 1099.93
   127.8 1095.74   131.1 1091.54   134.4  1085.7  138.061080.594     141 1079.04
   146.9 1078.99   154.1 1079.55  157.571080.597   160.6 1081.44   173.8 1082.68
   180.5 1081.94   203.3 1083.35   249.2 1084.19   341.2 1088.28   357.9 1089.73
   414.6  1091.7     428  1092.8   444.6  1095.5   487.1    1095   575.7 1098.48
#Mann= 6 ,-1,0
       0      .1       0  138.06    .045       0  157.57      .1       0
   202.5     .06       0   292.5     .07       0   507.5     .06       0
Bank Sta=138.06,157.57
XS Rating Curve= 0 ,0
Exp/Cntr(USF)=0,0
Exp/Cntr=0.3,0.1

Type RM Length L Ch R = 1 ,1365    ,619.7,621.5,608.8
XS GIS Cut Line= 3
1674007.10336119484467.4821232491674055.66980429484895.194078652
1674115.77040906485123.718249045
#Sta/Elev= 30
       0 1118.31    21.4 1118.33    30.4 1116.89    54.4  1100.5      61 1097.81
    97.3    1095   150.6 1089.09   192.1 1079.71  212.221079.034   222.8 1077.65
   239.3 1078.11  243.551079.035   252.5 1080.39   348.2 1080.08   387.8 1081.87
   454.5 1081.81   485.1 1082.84   491.9    1085     502 1092.38   515.6 1100.67
   539.4 1102.06   542.8    1104   552.9 1113.04   556.3 1115.07   576.7 1116.46
   583.5 1120.62   600.4 1125.38   627.6 1125.08   641.1 1130.69   666.8 1132.53
#Mann= 4 ,-1,0
       0      .1       0  212.22    .045       0  243.55     .05       0
     340     .06       0
Bank Sta=212.22,243.55
XS Rating Curve= 0 ,0
Exp/Cntr(USF)=0,0
Exp/Cntr=0.3,0.1

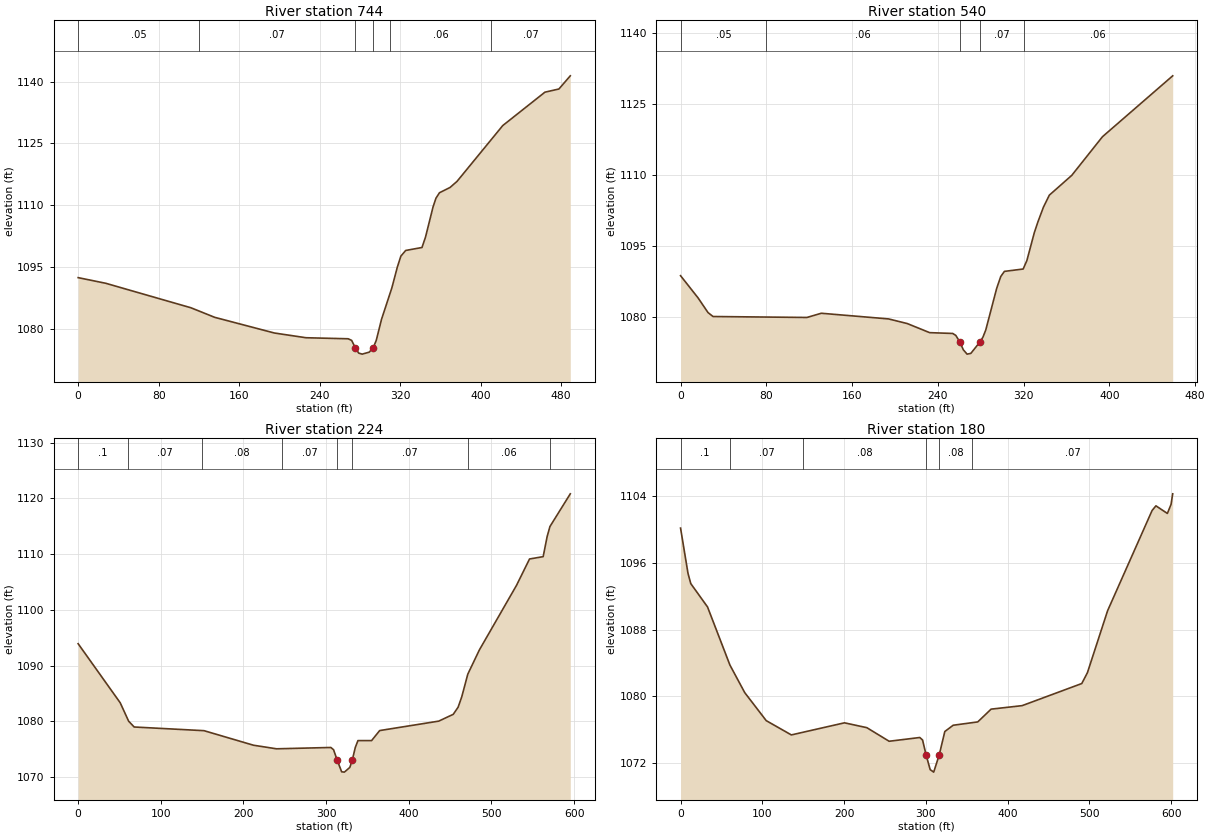
Type RM Length L Ch R = 1 ,744     ,203.8,204.3,203.7
XS GIS Cut Line= 2
1673604.77810235484754.9118736931673772.08393087485214.480035924
#Sta/Elev= 30
       0 1092.38    27.4 1091.01   112.1 1085.06   135.7 1082.74     195 1078.93
   226.5 1077.78   268.3 1077.53   271.8 1077.14  275.351075.398   278.8 1074.05
   282.3  1073.8   289.3 1074.28  293.311075.397   296.3 1077.16   301.5 1082.25
   311.8 1089.91   317.2 1094.92   320.7 1097.59   325.5 1098.98   341.7  1099.7
   345.2 1102.21   352.7 1109.55   355.6 1111.67   359.1    1113   369.6 1114.28
   376.6 1115.78     422 1129.32   463.9 1137.43   477.8  1138.2   489.1  1141.4
#Mann= 6 ,-1,0
       0     .05       0     120     .07       0  275.35    .045       0
  293.31     .07       0     310     .06       0     410     .07       0
Bank Sta=275.35,293.31
XS Rating Curve= 0 ,0
Exp/Cntr(USF)=0,0
Exp/Cntr=0.3,0.1

Type RM Length L Ch R = 1 ,540     ,309.7,316.1,318.9
XS GIS Cut Line= 2
1673416.64995118484824.3957401151673571.74634221485256.508131176
#Sta/Elev= 30
       0 1088.64    16.3 1083.96    25.6 1080.85    30.3 1080.01   117.9 1079.81
   131.3  1080.7   194.1  1079.5   211.5 1078.52   232.4  1076.6   253.9 1076.43
   256.8 1076.01  260.511074.632   263.8 1072.97   267.3 1072.06   270.8 1072.22
   279.31074.629   282.1 1075.66   284.7 1077.15   294.9 1085.96   298.7 1088.47
   302.1 1089.55   319.6 1090.05   323.1 1091.86     330 1097.73   333.5  1100.1
   338.5 1103.12     344 1105.66   364.9 1109.84   393.6 1118.02   459.1 1130.89
#Mann= 5 ,-1,0
       0     .05       0      80     .06       0  260.51    .045       0
   279.3     .07       0     320     .06       0
Bank Sta=260.51,279.3
XS Rating Curve= 0 ,0
Exp/Cntr(USF)=0,0
Exp/Cntr=0.3,0.1

Type RM Length L Ch R = 1 ,224     ,62.1,64.3,62.2
XS GIS Cut Line= 4
 1673173.4192096484898.5603747381673229.82445481485128.250020123
1673221.41267702485302.7944092861673332.03532732485449.972887323
#Sta/Elev= 30
       0 1093.94    50.9 1083.35    61.1 1080.05    67.8 1079.01   152.3 1078.35
   212.2 1075.74     240  1075.1   305.7 1075.34     309 1074.94   313.5 1073.03
   318.8 1070.98   322.1 1070.92   328.7 1071.77  331.59 1073.04   335.3 1075.34
   338.5 1076.57     355 1076.57   364.8 1078.37   436.2 1080.06   453.8 1081.28
   459.7 1082.56   464.1 1084.42   471.4 1088.48   485.4 1092.82   530.3 1104.39
   546.1 1109.13   562.6 1109.55   567.4 1113.15   570.8 1114.95   595.4 1120.81
#Mann= 8 ,-1,0
       0      .1       0      60     .07       0     150     .08       0
  246.51     .07       0   313.5    .045       0  331.59     .07       0
  471.26     .06       0  571.26     .07       0
Bank Sta=313.5,331.59
XS Rating Curve= 0 ,0
Exp/Cntr(USF)=0,0
Exp/Cntr=0.3,0.1

Type RM Length L Ch R = 1 ,180     ,159.3,159.3,159.3
XS GIS Cut Line= 5
1673125.66811834484906.4570973111673198.71291943485157.376520897
1673175.51778404485241.9558724681673173.66158576485310.691131859
1673284.28423606485457.869609896
#Sta/Elev= 30
       0 1100.16     9.1 1094.74    12.5 1093.51      33 1090.71    60.4 1083.74
    78.5 1080.44   104.8 1077.08   135.5 1075.37   200.5 1076.82   227.8 1076.24
   255.1 1074.61   292.6 1075.06     296 1074.76   300.3 1072.97   305.3 1071.21
   309.6 1070.91   316.4 1072.99   323.2 1075.78   333.4 1076.53   363.5 1076.93
   379.8 1078.46   417.8 1078.88   490.7 1081.53   497.6 1082.83   522.3 1090.26
   576.7 1102.27   581.4 1102.83   595.4 1101.92   599.9 1103.01   601.9 1104.27
#Mann= 6 ,-1,0
       0      .1       0      60     .07       0     150     .08       0
   300.3    .045       0   316.4     .08       0  356.51     .07       0
Bank Sta=300.3,316.4
XS Rating Curve= 0 ,0
Exp/Cntr(USF)=0,0
Exp/Cntr=0.3,0.1