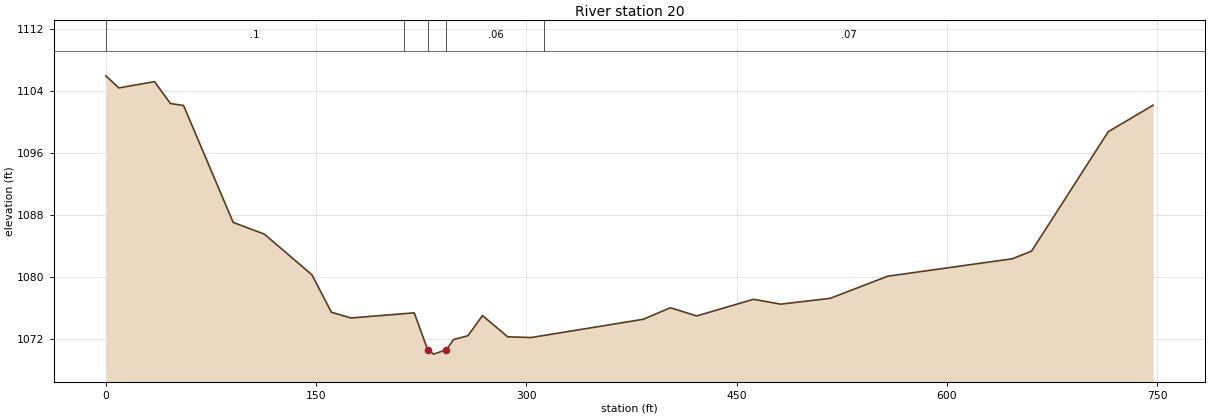
HEC-RAS study GraveCk2.prj: GraveCk2

--- GraveCk2.g01 (geometry) --- (continued)

Type RM Length L Ch R = 1 ,20      ,,,
XS GIS Cut Line= 4
 1672995.9668469484913.7573671351673101.72030542 485009.61588406
1673018.44046005485246.7898820421672708.62926763485416.096628704
#Sta/Elev= 30
       0 1105.96     9.2  1104.4    34.7 1105.21    46.1 1102.38    55.4 1102.14
    90.8 1087.07     113 1085.56     147 1080.32   160.9 1075.49   174.8 1074.75
     220 1075.41  229.58 1070.67   233.9 1070.09     243 1070.67   248.1 1071.97
   258.3 1072.46   268.7 1075.06   286.7 1072.32   303.5 1072.23   383.4 1074.58
   402.8 1076.07   421.5 1075.01   462.1 1077.16   481.4 1076.53   516.8 1077.28
   557.8 1080.13   646.8 1082.38   660.5 1083.37   715.2 1098.76 747.158 1102.17
#Mann= 5 ,-1,0
       0      .1       0  212.73     .06       0  229.58    .045       0
     243     .06       0  312.73     .07       0
Bank Sta=229.58,243
XS Rating Curve= 0 ,0
Exp/Cntr(USF)=0,0
Exp/Cntr=0.3,0.1
LCMann Table=0

Chan Stop Cuts=-1
Use User Specified Reach Order=0
Composite Channel Slope=5